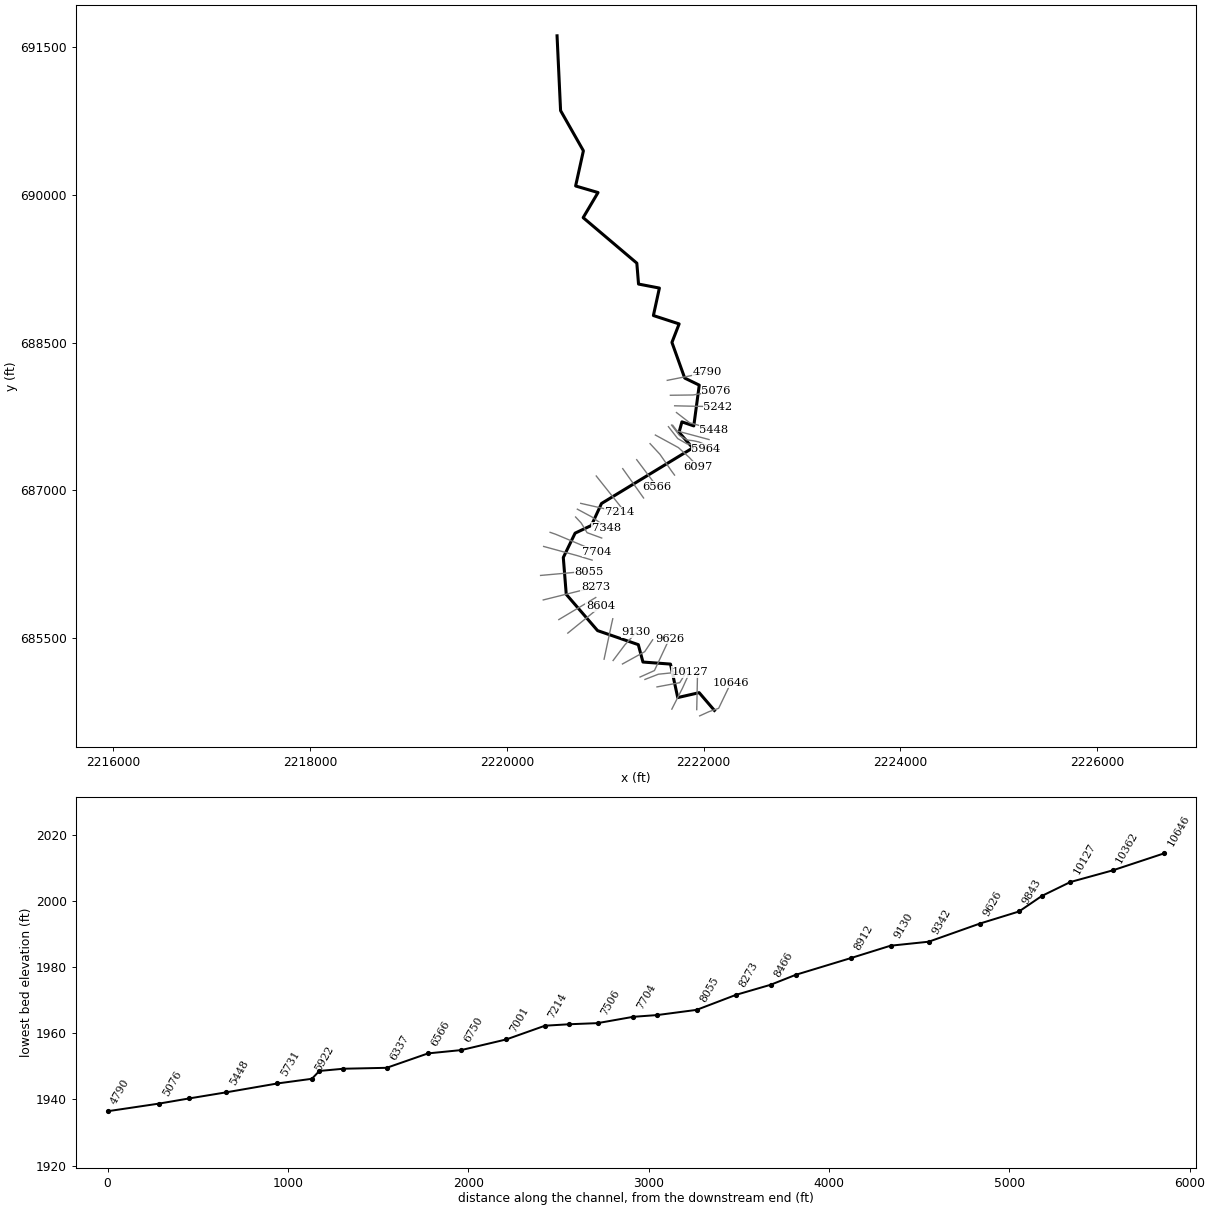
--- OSBORNERN.prj (project) ---

Proj Title=OSBORNERN
Current Plan=p01
Default Exp/Contr=0,0
English Units
Geom File=g01
Flow File=f01
Plan File=p01
BEGIN DESCRIPTION:
----------MODELED AS PART OF WVEMD CTP PROGRAM, 2022---------
AFH study: Osborne Run
Upshur County, WV
HEC-RAS Version: RAS 6.3
Vertical Datum: NAVD88
Projection: NAD 1983 StatePlane West Virginia S FIPS 4702 (US Feet)
Terrain: 1-meter LIDAR (FEMA Region III 3DEP collected 2016-2018)
Land Use: 2019 NLCD
Hydrologic Method:
WV SIR2010-5033 regression equations
Additional Model Notes:
None
END DESCRIPTION:
DSS Export Rating Curves= 0
DSS Export Rating Curve Sorted= 0
DSS Export Volume Flow Curves= 0
DXF OffsetX= 0
DXF OffsetY= 0
DXF ScaleX= 0
DXF ScaleY= 0

--- OSBORNERN.p01 (plan) ---

Plan Title=Floodplain
Program Version=4.00
Geom File=g01
Flow File=f01
K Sum by GR=0
Std Step Tol=0.01
Critical Tol=0.01
Num of Std Step Trials=20
Max Error Tol=0.3
Flow Tol Ratio=0.001
Split Flow NTrial=30
Split Flow Tol=0.02
Split Flow Ratio=0.02
Log Output Level=0
Friction Slope Method=1
Unsteady Friction Slope Method=2
Unsteady Bridges Friction Slope Method=1
Global Log Level=0
CheckData=False
Run HTab=0
Run UNet=0
Run PostProcess=0
UNET Theta=0
UNET Theta Warmup=0
UNET ZTol=0
UNET ZSATol=0
UNET MxIter=0
UNET MaxInSteps=0
UNET DtIC=0
UNET DtMin=0
UNET MaxCRTS=0
UNET WFStab=0
UNET SFStab=0
UNET WFX=0
UNET SFX=0
UNET DSS MLevel=0
UNET DZMax Abort=0
UNET Convert EG Bridges=0
UNET Use Existing IB Tables=0
UNET Froude Limit=0
UNET Froude Power=0
Write IC File=0
Echo Input=False
Echo Output=False
Write Detailed=0

--- OSBORNERN.f01 (steady flow) ---

Flow Title=Flows
Program Version=6.30
Number of Profiles= 1
Profile Names=01pct
River Rch & RM=OSBORNERN,Main,10646
     325
River Rch & RM=OSBORNERN,Main,8604
     363
River Rch & RM=OSBORNERN,Main,5448
     424
River Rch & RM=OSBORNERN,Main,4136
     473
Boundary for River Rch & Prof#=OSBORNERN,Main            , 1
Up Type= 0
Dn Type= 3
Dn Slope=0.0324
DSS Import GetInterval= 0
DSS Import GetPeak= 0
DSS Import FillOption= 0

--- OSBORNERN.g01 (geometry) ---

Geom Title=Geometry
Program Version=6.31

River Reach=OSBORNERN       ,Main
Reach XY= 30
2222108.87200002684761.2249999942221953.88600002684941.909000009
2221736.00000003      684892.0592221662.34200002685232.307999998
2221382.44500001685253.1980000142221335.11300002685429.875000015
     2220921.206685572.5849999932220602.79099999685941.250000015
2220572.88700001686315.638000011     2220692.933686563.456000015
2220858.27900003 686641.321000012220961.09700002686864.614999995
2221888.29700002687429.302000016     2221749.479687588.266000003
2221778.46700004687694.347000018     2221899.028687653.311000019
2221954.65800001688067.6190000032221806.96900003688139.361000001
     2221676.936688501.8729999962221750.19400004688689.854000017
2221488.55400002 688775.01700002     2221549.565689054.283999994
     2221337.517 689095.005000012221320.14700003689307.481999993
2220774.69000004      689770.0372220925.81299998 690025.23800002
      2220697.97690091.914000019     2220777.065690449.762000009
2220545.24400002690858.0610000042220509.33017669691618.140757786

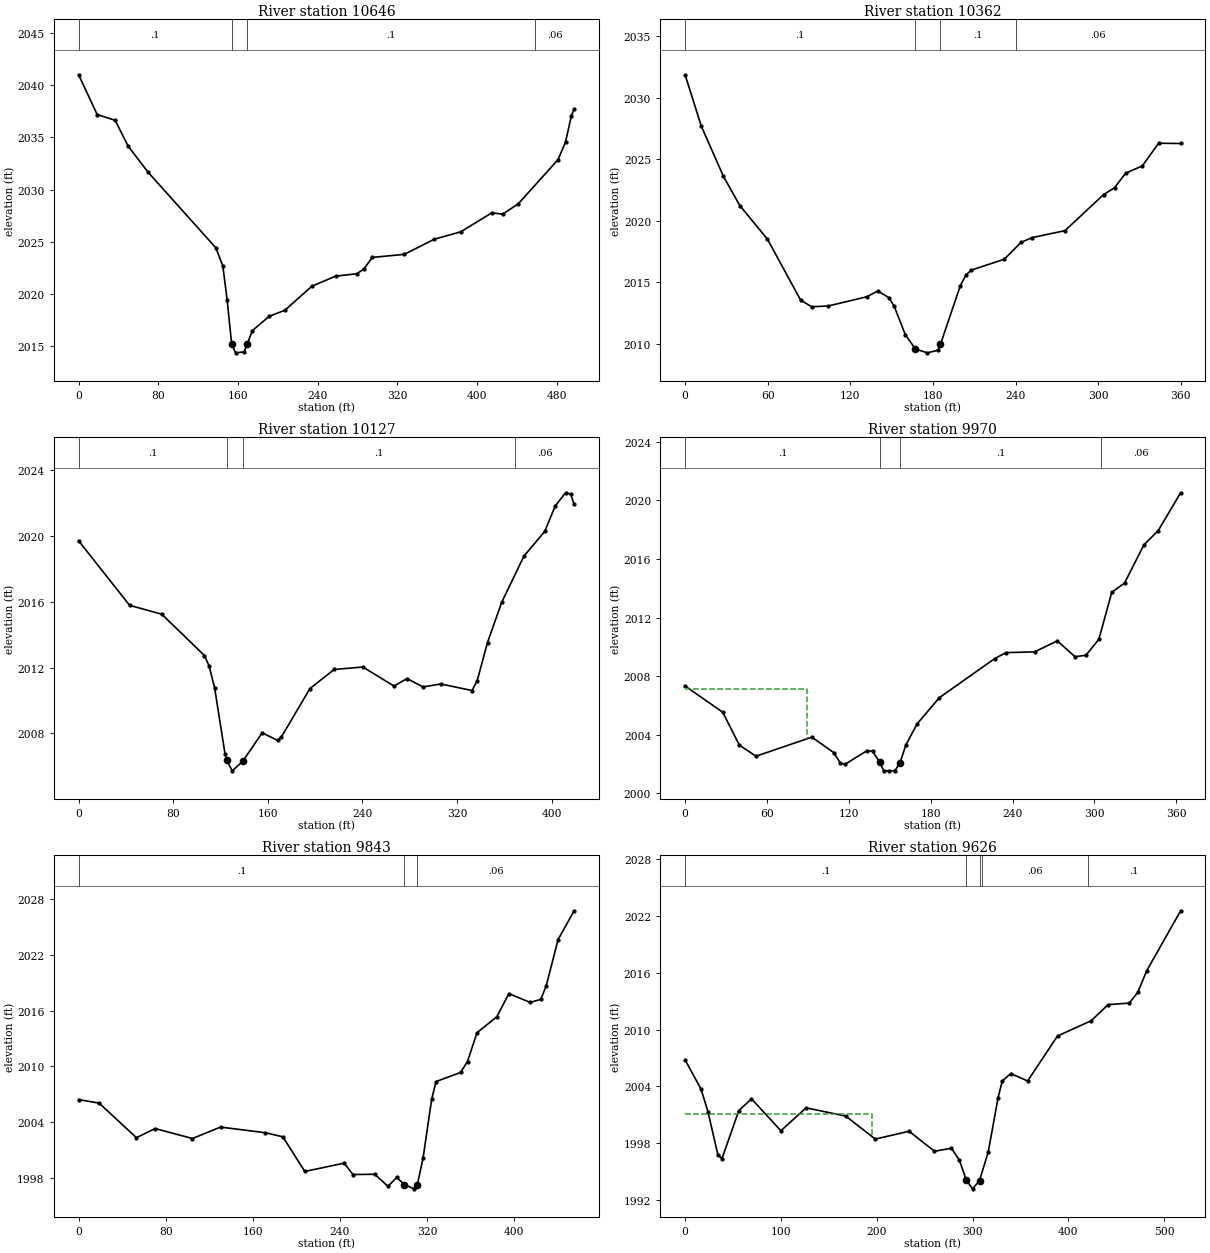
Type RM Length L Ch R = 1 ,10646   ,284.2,284.2,284.2
XS GIS Cut Line= 4
2221958.88710019684705.8414063492222053.74968629684748.960763664
2222151.74822564684782.6722612022222277.18635601 685043.74037004
#Sta/Elev= 30
       0 2040.98    18.6 2037.18    36.7 2036.62    49.7 2034.15    69.9 2031.64
   137.8 2024.42   144.8 2022.68   149.1 2019.44   153.62015.247   157.5 2014.38
     166 2014.47   169.2 2015.21   174.4  2016.5   191.4 2017.88     207 2018.45
     234 2020.74     258 2021.72     279 2021.94   286.1 2022.37   294.9 2023.51
   326.9  2023.8   357.1 2025.25   383.7 2025.96   414.8 2027.77   425.8 2027.65
   441.4 2028.64   481.3 2032.86   488.8 2034.54   494.6 2037.02   497.5 2037.72
#Mann= 4 ,-1,0
       0      .1       0   153.6    .045       0   169.2      .1       0
  457.84     .06       0
Bank Sta=153.6,169.2
XS Rating Curve= 0 ,0
Exp/Cntr(USF)=0,0
Exp/Cntr=0.3,0.1

Type RM Length L Ch R = 1 ,10362   ,237.8,235.1,227.3
XS GIS Cut Line= 2
2221929.09554423 684769.344459852221936.93542738685129.195096357
#Sta/Elev= 30
       0 2031.87    11.8 2027.68    27.8 2023.62    39.8 2021.22    59.8  2018.5
    83.9 2013.54    91.9    2013   103.9 2013.06   131.9 2013.81   139.9 2014.28
   147.9 2013.75   151.9 2013.03   159.9 2010.73   167.3 2009.56   175.9 2009.25
   183.9 2009.47  185.462009.938   199.9 2014.72   203.9 2015.57   207.9 2015.98
   231.9 2016.87   243.9 2018.23   251.9 2018.62   275.9 2019.19   303.9 2022.12
   311.9 2022.68   319.9 2023.86   332.1 2024.46   343.9  2026.3   359.9 2026.28
#Mann= 4 ,-1,0
       0      .1       0   167.3    .045       0  185.46      .1       0
     240     .06       0
Bank Sta=167.3,185.46
XS Rating Curve= 0 ,0
Exp/Cntr(USF)=0,0
Exp/Cntr=0.3,0.1

Type RM Length L Ch R = 1 ,10127   ,167.1,157,145.5
XS GIS Cut Line= 3
2221676.02218043684774.7743048452221784.21256788684988.019126479
2221858.69145778685151.872684278
#Sta/Elev= 30
       0  2019.7    43.1 2015.78    70.3 2015.24   106.4 2012.73   110.3  2012.1
     115 2010.77   123.8 2006.76   125.32006.356   129.9 2005.72   138.8  2006.3
   155.2 2008.03   168.3 2007.57   171.5 2007.78   195.6 2010.72   216.1 2011.88
   240.4 2012.03   266.8 2010.87   277.7 2011.33   291.3 2010.82   306.3    2011
   332.7  2010.6   337.1  2011.2   345.8 2013.52   357.8 2015.96   376.6 2018.77
   394.2 2020.27   403.1 2021.82   411.8 2022.62   416.1 2022.54   419.1 2021.91
#Mann= 4 ,-1,0
       0      .1       0   125.3    .045       0   138.8      .1       0
  369.12     .06       0
Bank Sta=125.3,138.8
XS Rating Curve= 0 ,0
Exp/Cntr(USF)=0,0
Exp/Cntr=0.3,0.1

Type RM Length L Ch R = 1 ,9970    ,126.8,127.3,124.1
XS GIS Cut Line= 3
2221525.06195035 685000.389795322221756.27935458685043.406986806
2221824.03143117685152.025395308
#Sta/Elev= 30
       0 2007.33    27.6 2005.54    39.8 2003.29      52 2002.54    92.9 2003.84
     109 2002.78   113.7 2002.08   117.1 2001.98   133.4 2002.92   137.4 2002.88
  142.652002.126   145.6 2001.55   149.6 2001.54   153.7 2001.55   157.4 2002.06
   161.8  2003.3     170 2004.74   186.3 2006.53   226.9  2009.2   235.2 2009.61
   256.1 2009.66   272.8 2010.41   285.8 2009.33   293.8 2009.43   303.3 2010.53
   312.7 2013.72   322.1 2014.36   336.3 2016.97   346.7 2017.93   363.2 2020.52
#Mann= 4 ,-1,0
       0      .1       0  142.65    .045       0   157.4      .1       0
  305.18     .06       0
#XS Ineff= 2 , 0
        89.45721 2007.12
Permanent Ineff=
       T       F
Bank Sta=142.65,157.4
XS Rating Curve= 0 ,0
Exp/Cntr(USF)=0,0
Exp/Cntr=0.3,0.1

Type RM Length L Ch R = 1 ,9843    ,204.1,216.8,228.2
XS GIS Cut Line= 4
2221402.66728627685076.368909782 2221539.4296923685129.505895565
2221740.31187763685150.1392773382221837.66788088685193.687545262
#Sta/Elev= 30
       0 2006.43    18.8 2006.05    53.1 2002.33    70.3 2003.31   104.6 2002.24
   130.4 2003.47   171.6 2002.86   187.7 2002.42   207.8 1998.69     244 1999.59
     252 1998.36   272.1 1998.39   284.2 1997.09   292.2 1998.05   299.4 1997.28
   308.3 1996.82   311.2 1997.26   316.4 2000.09   324.4 2006.48   328.4 2008.37
   350.9 2009.35   357.3 2010.53     366 2013.63   384.2 2015.34   395.3 2017.84
   414.9 2016.89   424.7 2017.23   429.6 2018.67   440.5 2023.66   455.3 2026.76
#Mann= 3 ,-1,0
       0      .1       0   299.4    .045       0   311.2     .06       0
Bank Sta=299.4,311.2
XS Rating Curve= 0 ,0
Exp/Cntr(USF)=0,0
Exp/Cntr=0.3,0.1

Type RM Length L Ch R = 1 ,9626    ,291.1,283.8,271.6
XS GIS Cut Line= 3
2221353.02571284685100.7850162542221499.17662091685166.601319228
 2221650.7103969685489.703093782
#Sta/Elev= 30
       0 2006.79    16.6 2003.72    23.9 2001.31    34.2 1996.77    38.5 1996.37
    56.1 2001.44    69.3 2002.68     100 1999.31   126.3 2001.73   167.6 2000.86
   198.5 1998.43   233.8 1999.25   260.3 1997.14     278 1997.46   286.3 1996.19
   293.61994.064   300.1 1993.17   307.3 1994.05   316.4 1997.06   326.6 2002.77
     331 2004.56   339.9 2005.35   357.5 2004.57   388.7 2009.32   423.8 2010.93
   441.5 2012.63   463.6  2012.8   472.4 2013.92   481.8 2016.21   517.2 2022.55
#Mann= 5 ,-1,0
       0      .1       0   293.6    .045       0   307.3      .1       0
  310.29     .06       0  420.29      .1       0
#XS Ineff= 2 , 0
           194.7 2001.08
Permanent Ineff=
       T       F
Bank Sta=293.6,307.3
XS Rating Curve= 0 ,0
Exp/Cntr(USF)=0,0
Exp/Cntr=0.3,0.1

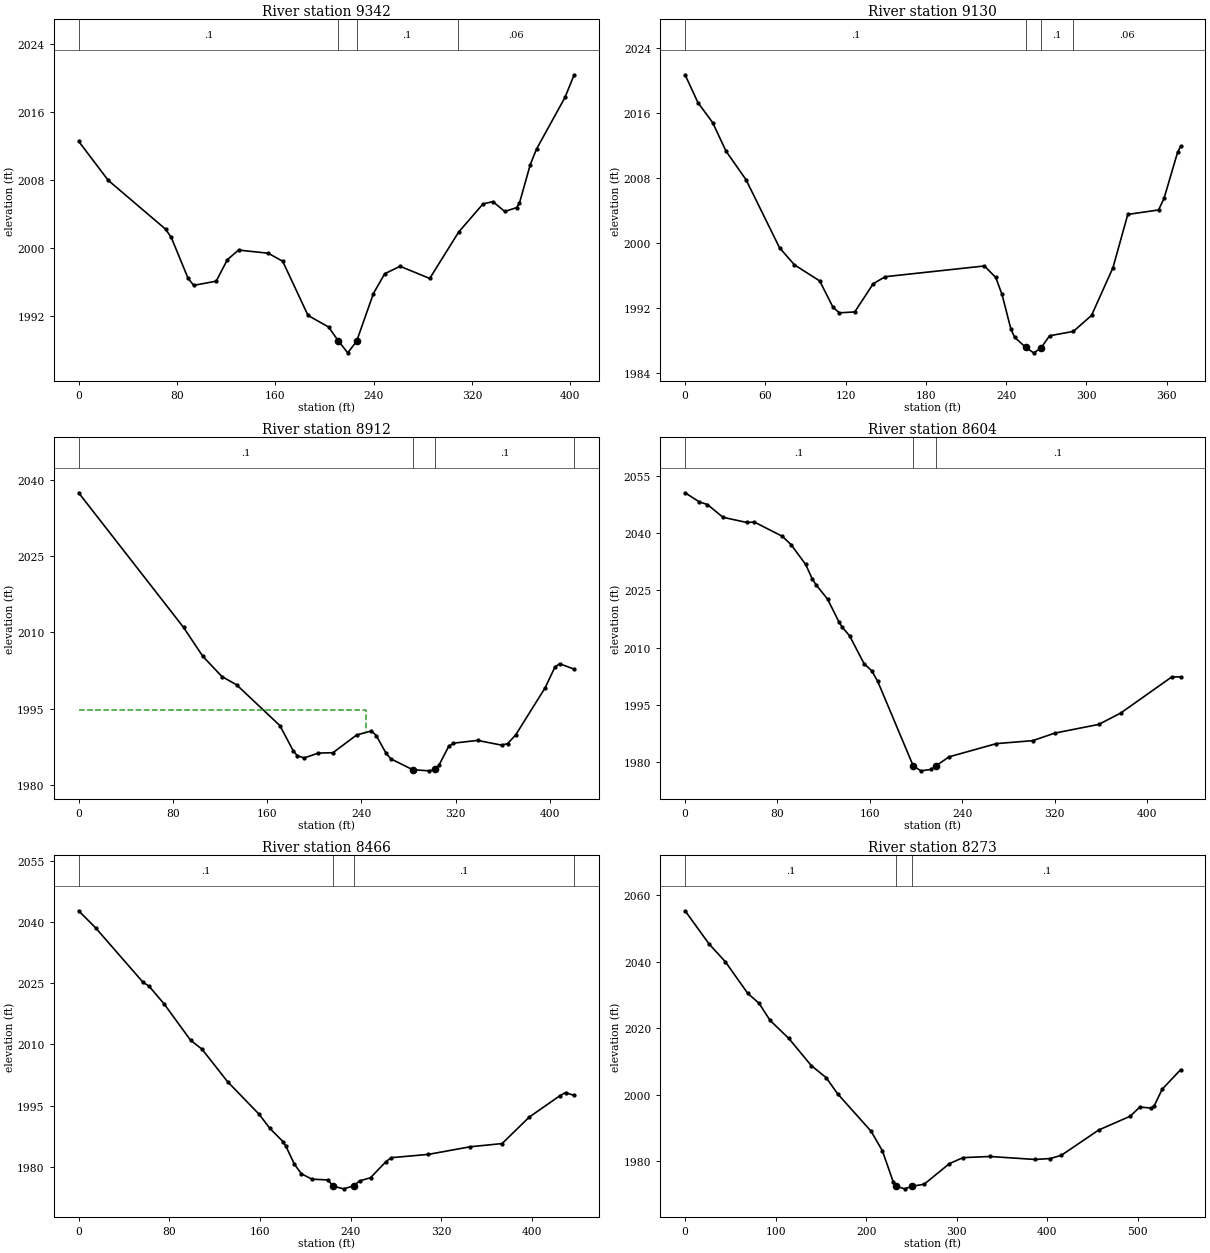
Type RM Length L Ch R = 1 ,9342    ,205.8,211.8,214.9
XS GIS Cut Line= 3
2221174.30055265685233.4951693632221400.38517326685358.563257359
 2221480.9578838685478.821034278
#Sta/Elev= 30
       0 2012.57    24.1 2007.97    70.7 2002.23    75.3 2001.27      89 1996.46
    93.6 1995.62   111.9 1996.11     121 1998.64   130.1 1999.77   154.2  1999.4
     166 1998.45   186.6 1992.08   203.3 1990.72   211.11989.118   218.9 1987.68
   226.1 1989.03   239.8 1994.66     249 1996.99   261.5 1997.86   285.6 1996.43
   309.1 2001.88   328.9 2005.19     337 2005.47   346.6 2004.31   356.2 2004.76
   358.6  2005.3   367.4 2009.83   372.5 2011.66   395.6 2017.72   403.1 2020.39
#Mann= 4 ,-1,0
       0      .1       0   211.1    .045       0   226.1      .1       0
  308.37     .06       0
Bank Sta=211.1,226.1
XS Rating Curve= 0 ,0
Exp/Cntr(USF)=0,0
Exp/Cntr=0.3,0.1

Type RM Length L Ch R = 1 ,9130    ,209.9,218.1,224.2
XS GIS Cut Line= 3
2221079.11369294 685268.744830522221199.13165719685428.446153911
2221314.31018739685554.271439007
#Sta/Elev= 30
       0 2020.72     9.6 2017.29    20.6 2014.83    30.6 2011.31    45.6 2007.78
    70.6 1999.41    81.7 1997.31   100.6 1995.33   110.6 1992.07   115.3  1991.4
   126.8 1991.51   140.6 1994.98   149.6 1995.85   223.7 1997.17   232.2 1995.75
   236.9 1993.66   243.5 1989.41   246.3 1988.39   254.6 1987.15   260.5 1986.47
   265.8 1987.01   272.4 1988.57   290.2 1989.11   303.8 1991.08   319.8 1996.95
   330.9 2003.52   353.9 2004.07     358  2005.5   368.1 2011.16   370.4 2011.91
#Mann= 4 ,-1,0
       0      .1       0   254.6    .045       0   265.8      .1       0
  289.77     .06       0
Bank Sta=254.6,265.8
XS Rating Curve= 0 ,0
Exp/Cntr(USF)=0,0
Exp/Cntr=0.3,0.1

Type RM Length L Ch R = 1 ,8912    ,316,307.8,291.9
XS GIS Cut Line= 3
2220987.31196737685282.1086314782221064.98189645685646.559837123
2221075.73619432685693.161794566
#Sta/Elev= 30
       0 2037.41      89 2010.96   105.4 2005.26   121.7 2001.27     134 1999.68
   170.8 1991.65     182 1986.75   185.4 1985.77   191.3 1985.29   203.5 1986.25
   215.8 1986.32   235.9 1989.81   248.5  1990.6   252.6 1989.69   260.8 1986.24
   264.9 1985.12   283.5 1982.98   297.6 1982.76   302.51983.037   305.8 1983.88
     314 1987.56   318.1  1988.2   338.5 1988.74     359 1987.81     364 1988.11
   370.8 1989.79   395.8 1999.06   404.2 2003.17   408.2 2003.81   420.5 2002.74
#Mann= 4 ,-1,0
       0      .1       0   283.5    .045       0   302.5      .1       0
  420.46     .06       0
#XS Ineff= 2 , 0
          244.23 1994.62
Permanent Ineff=
       F       F
Bank Sta=283.5,302.5
XS Rating Curve= 0 ,0
Exp/Cntr(USF)=0,0
Exp/Cntr=0.3,0.1

Type RM Length L Ch R = 1 ,8604    ,139.9,138.7,134.4
XS GIS Cut Line= 2
2220618.70962329685547.3679671222220951.82366535 685817.94796519
#Sta/Elev= 30
       0  2050.6    12.2 2048.23    19.4 2047.51    32.8 2044.17    53.4 2042.81
      60 2042.92    84.3 2039.17    91.7 2037.03   104.4 2031.81   110.1 2028.03
   113.2 2026.54   123.4 2022.71   133.1 2016.81     136 2015.36   142.4 2013.12
   155.1 2005.72   161.6 2003.94   166.8 2001.15   197.61978.954   204.2 1977.66
   212.8 1978.02   217.2 1978.95   228.6 1981.33   269.6  1984.8   301.1 1985.58
   320.1 1987.55   358.2 1989.83   377.2  1992.8   421.6 2002.31   429.2  2002.3
#Mann= 3 ,-1,0
       0      .1       0   197.6    .045       0   217.2      .1       0
Bank Sta=197.6,217.2
XS Rating Curve= 0 ,0
Exp/Cntr(USF)=0,0
Exp/Cntr=0.3,0.1

Type RM Length L Ch R = 1 ,8466    ,194.7,192.1,184.6
XS GIS Cut Line= 2
2220527.38639663685684.6840869872220902.76000177685909.061542691
#Sta/Elev= 30
       0 2042.74    14.9 2038.59    56.8 2025.24    62.2 2024.26    75.5 2019.92
    98.8 2011.04   108.9 2008.85   131.4 2000.91   159.4 1992.88   168.7 1989.49
   180.3 1986.23   182.7 1985.22   190.5 1980.65   196.6 1978.35     206 1977.02
   219.9 1976.84   224.6 1975.32   233.9 1974.66   242.6 1975.39   247.9 1976.59
   257.6 1977.39   271.2 1981.31   275.9 1982.29   308.5 1983.09   345.8 1984.97
   373.7 1985.74   397.6 1992.21     425 1997.51   429.7 1998.22   437.3 1997.53
#Mann= 4 ,-1,0
       0      .1       0   224.6    .045       0   242.6      .1       0
  437.32     .06       0
Bank Sta=224.6,242.6
XS Rating Curve= 0 ,0
Exp/Cntr(USF)=0,0
Exp/Cntr=0.3,0.1

Type RM Length L Ch R = 1 ,8273    ,219.8,218.2,213.9
XS GIS Cut Line= 2
2220369.02749506685884.2840307372220899.92972777686016.853236373
#Sta/Elev= 30
       0 2055.32    26.4 2045.36    44.5 2039.96    69.2 2030.45    81.6 2027.49
    93.9 2022.31   114.6 2016.87   139.3 2008.72   155.8 2005.08   168.3 2000.26
   205.3 1988.97   217.8 1983.12     230 1973.56  232.691972.458   242.4 1971.61
   250.6 1972.38     264    1973   291.8 1979.19   306.8    1981   336.5 1981.35
   386.7 1980.45   403.2 1980.73   415.5 1981.71   456.8 1989.33   491.6 1993.48
   502.1 1996.23   514.5 1995.93     518 1996.59   526.8  2001.6   547.2 2007.48
#Mann= 3 ,-1,0
       0      .1       0  232.69    .045       0   250.6      .1       0
Bank Sta=232.69,250.6
XS Rating Curve= 0 ,0
Exp/Cntr(USF)=0,0
Exp/Cntr=0.3,0.1

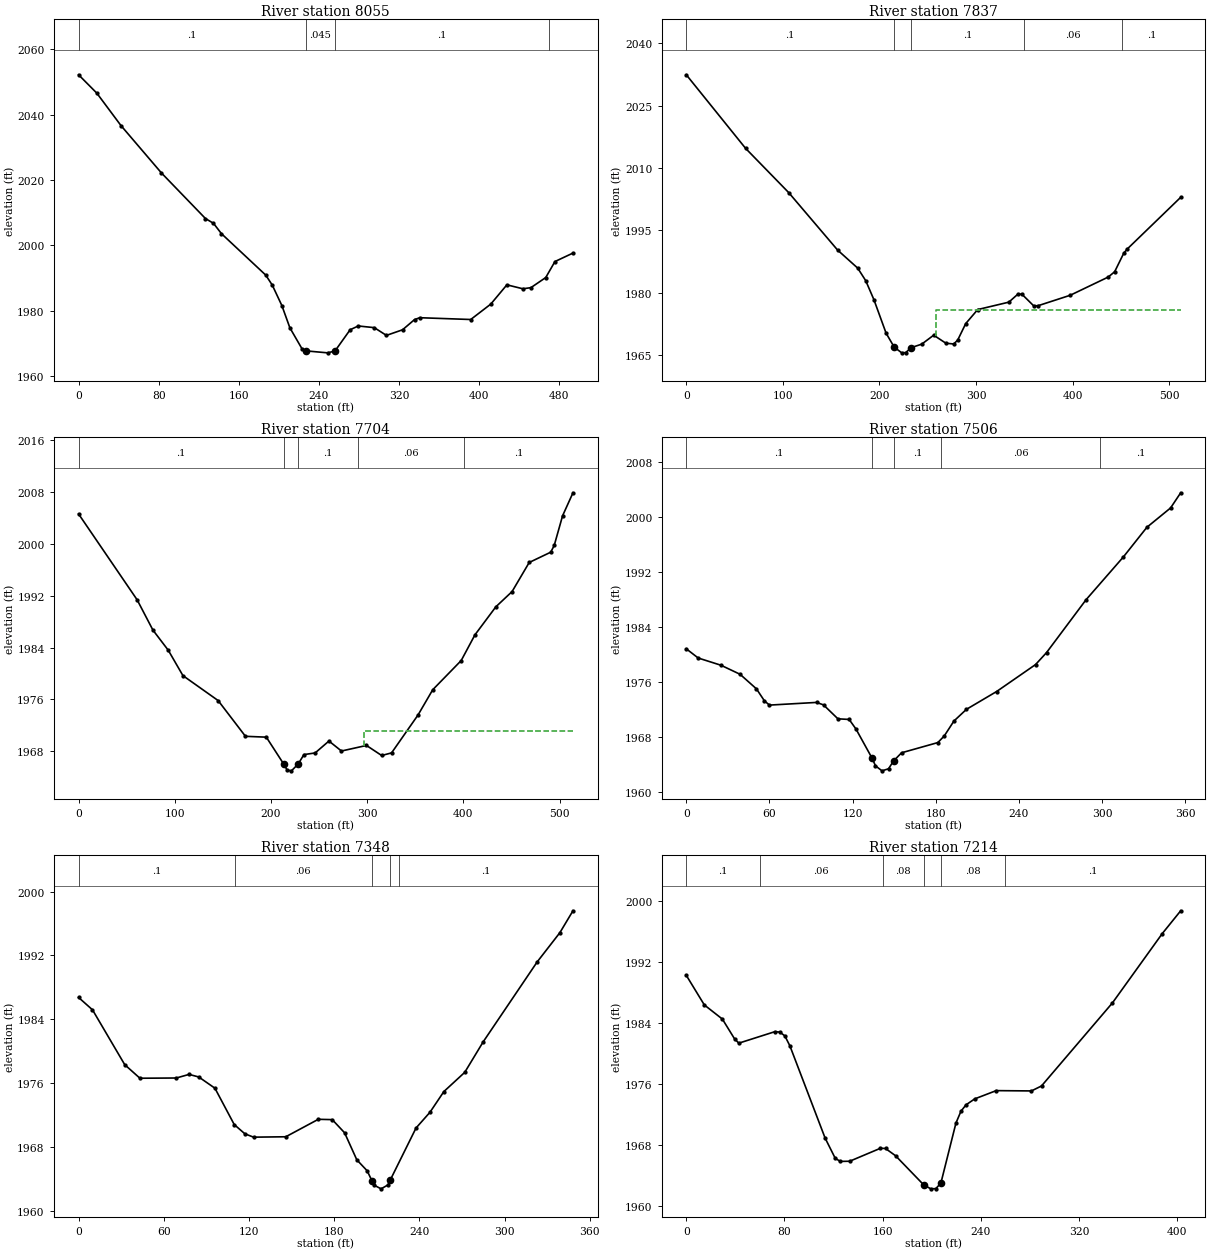
Type RM Length L Ch R = 1 ,8055    ,223.8,218.5,212.9
XS GIS Cut Line= 3
2220342.02345311686133.4180952272220690.46270414 686164.77762782
2220834.19389519686171.746412841
#Sta/Elev= 30
       0 2052.16    18.2 2046.55    42.3 2036.63    82.8  2022.1   126.7 2008.17
   134.7 2006.71   142.7 2003.53   186.9 1990.86   193.4 1987.81     203 1981.54
     211 1974.73     223 1968.37   227.1 1967.67   248.6 1967.07  256.02 1967.62
   271.2 1974.14   279.3 1975.29   295.3 1974.78   307.4 1972.41   323.5 1974.12
   335.5 1977.25   340.7 1977.82   391.6 1977.27   411.6 1981.98   427.7 1987.88
   443.7 1986.67   451.7 1987.02   466.5 1990.11   475.7 1995.01   493.7  1997.6
#Mann= 4 ,-1,0
       0      .1       0   227.1    .045       0  256.02      .1       0
  469.85     .06       0
Bank Sta=227.1,256.02
XS Rating Curve= 0 ,0
Exp/Cntr(USF)=0,0
Exp/Cntr=0.3,0.1

Type RM Length L Ch R = 1 ,7837    ,134.5,132.9,131
XS GIS Cut Line= 3
2220372.97246178686428.1023296642220711.88809614686335.621293359
2220865.70660351686289.052387458
#Sta/Elev= 30
       0 2032.44    61.4 2014.73     106 2004.09   156.7 1990.24   177.5  1985.9
   185.8 1982.88   194.3  1978.3   206.9 1970.24   215.31966.876   223.1  1965.5
   227.2 1965.56     233 1966.76   243.8 1967.59   256.2 1969.75   268.8 1967.82
     277 1967.63   281.1 1968.59   289.4 1972.55   301.8 1975.92     334  1977.7
   343.3 1979.61   347.5 1979.63   359.7 1976.83   364.1 1976.83   397.6 1979.36
   436.9 1983.74   443.6 1985.02   452.9 1989.42   456.4 1990.44     512 2002.94
#Mann= 5 ,-1,0
       0      .1       0   215.3    .045       0     233      .1       0
     350     .06       0  451.31      .1       0
#XS Ineff= 2 , 0
                          258.25         1975.88
Permanent Ineff=
       F       F
Bank Sta=215.3,233
XS Rating Curve= 0 ,0
Exp/Cntr(USF)=0,0
Exp/Cntr=0.3,0.1

Type RM Length L Ch R = 1 ,7704    ,204.7,197.9,189.5
XS GIS Cut Line= 3
2220438.79773381686571.5771129332220496.29021023686551.541855998
2220914.14509492686376.212323429
#Sta/Elev= 30
       0 2004.63    60.9 1991.37    77.3  1986.7    93.2  1983.6   108.5 1979.67
   145.1 1975.82   173.5  1970.3   195.2 1970.17   213.51965.964   216.9 1965.08
   221.3 1964.97   228.3 1966.02   234.3 1967.48   245.9 1967.73   260.3 1969.57
   273.3 1968.03   299.3 1968.89   315.1 1967.34   325.4 1967.74   352.9 1973.59
   368.2 1977.49   397.8    1982   412.1 1985.97   433.8 1990.29   450.7 1992.65
   468.5 1997.14   490.9 1998.73   494.5 1999.77   503.2 2004.35     514  2007.9
#Mann= 5 ,-1,0
       0      .1       0   213.5    .045       0   228.3      .1       0
  290.88     .06       0  400.88      .1       0
#XS Ineff= 2 , 0
                          296.63         1971.05
Permanent Ineff=
       F       F
Bank Sta=213.5,228.3
XS Rating Curve= 0 ,0
Exp/Cntr(USF)=0,0
Exp/Cntr=0.3,0.1

Type RM Length L Ch R = 1 ,7506    ,151.3,157.7,161
XS GIS Cut Line= 4
2220697.71423028686727.4688338462220754.86697843686666.082548795
2220814.84208451 686568.005610612220963.01587601686513.675220392
#Sta/Elev= 30
       0 1980.84     8.6  1979.5      25 1978.45    38.8 1977.13    50.6 1975.01
    56.4 1973.25      60 1972.64      94 1973.03      99 1972.67   109.4 1970.64
   117.5 1970.55   122.4 1969.16  134.081964.887   136.5 1963.79   141.2 1963.06
   145.9 1963.36   149.5 1964.49   155.3 1965.69   181.5 1967.18   186.1 1968.14
   193.1 1970.32   202.1 1972.02   223.9 1974.62     252 1978.55   259.9 1980.29
   288.4 1987.99   315.3 1994.22   332.3 1998.55   349.4 2001.37   356.7 2003.58
#Mann= 5 ,-1,0
       0      .1       0  134.08    .045       0   149.5      .1       0
  183.87     .06       0  298.83      .1       0
Bank Sta=134.08,149.5
XS Rating Curve= 0 ,0
Exp/Cntr(USF)=0,0
Exp/Cntr=0.3,0.1

Type RM Length L Ch R = 1 ,7348    ,129.8,133.9,138.5
XS GIS Cut Line= 4
2220715.54253879686806.9879461152220861.59956185686728.879190308
 2220958.7592337686659.660861992 2221007.6565849686619.653938286
#Sta/Elev= 30
       0 1986.72     9.8 1985.17    32.5 1978.29    43.2 1976.59    68.8 1976.62
    77.8 1977.07    84.6 1976.75      96 1975.34   109.6 1970.78   117.1 1969.62
   123.2  1969.2   145.9 1969.25   168.8 1971.44   178.6  1971.4   187.3 1969.75
   195.9 1966.36   203.2 1964.98   206.5 1963.75   208.1 1963.18     213 1962.72
   217.9 1963.22   219.61963.877   237.6 1970.35   247.4 1972.32   257.2 1974.92
   271.9 1977.33   284.9 1981.16   322.9 1991.18   338.9 1994.85   348.1 1997.59
#Mann= 5 ,-1,0
       0      .1       0     110     .06       0   206.5    .045       0
   219.6     .06       0  225.63      .1       0
Bank Sta=206.5,219.6
XS Rating Curve= 0 ,0
Exp/Cntr(USF)=0,0
Exp/Cntr=0.3,0.1

Type RM Length L Ch R = 1 ,7214    ,216.4,213.8,203
XS GIS Cut Line= 2
2220749.88122698686866.0710477162221142.74648253686777.219038702
#Sta/Elev= 30
       0 1990.21    14.7 1986.34    29.4 1984.49    39.3 1981.91    42.8 1981.34
    72.1 1982.84    76.2 1982.79    80.3 1982.29    84.4 1980.99   113.1 1968.92
   121.3 1966.29   125.4 1965.87   133.1 1965.89   158.2 1967.59   162.3 1967.56
   170.5 1966.61   193.3 1962.82   199.2 1962.28   203.3 1962.31   207.4 1963.02
   219.7 1970.89   223.8 1972.44   227.9 1973.27     235 1974.05   252.5 1975.13
   281.2 1975.09   289.4 1975.74   347.2 1986.61   387.8 1995.68   402.8 1998.66
#Mann= 6 ,-1,0
       0      .1       0      60     .06       0     160     .08       0
   193.3    .045       0   207.4     .08       0     260      .1       0
Bank Sta=193.3,207.4
XS Rating Curve= 0 ,0
Exp/Cntr(USF)=0,0
Exp/Cntr=0.3,0.1

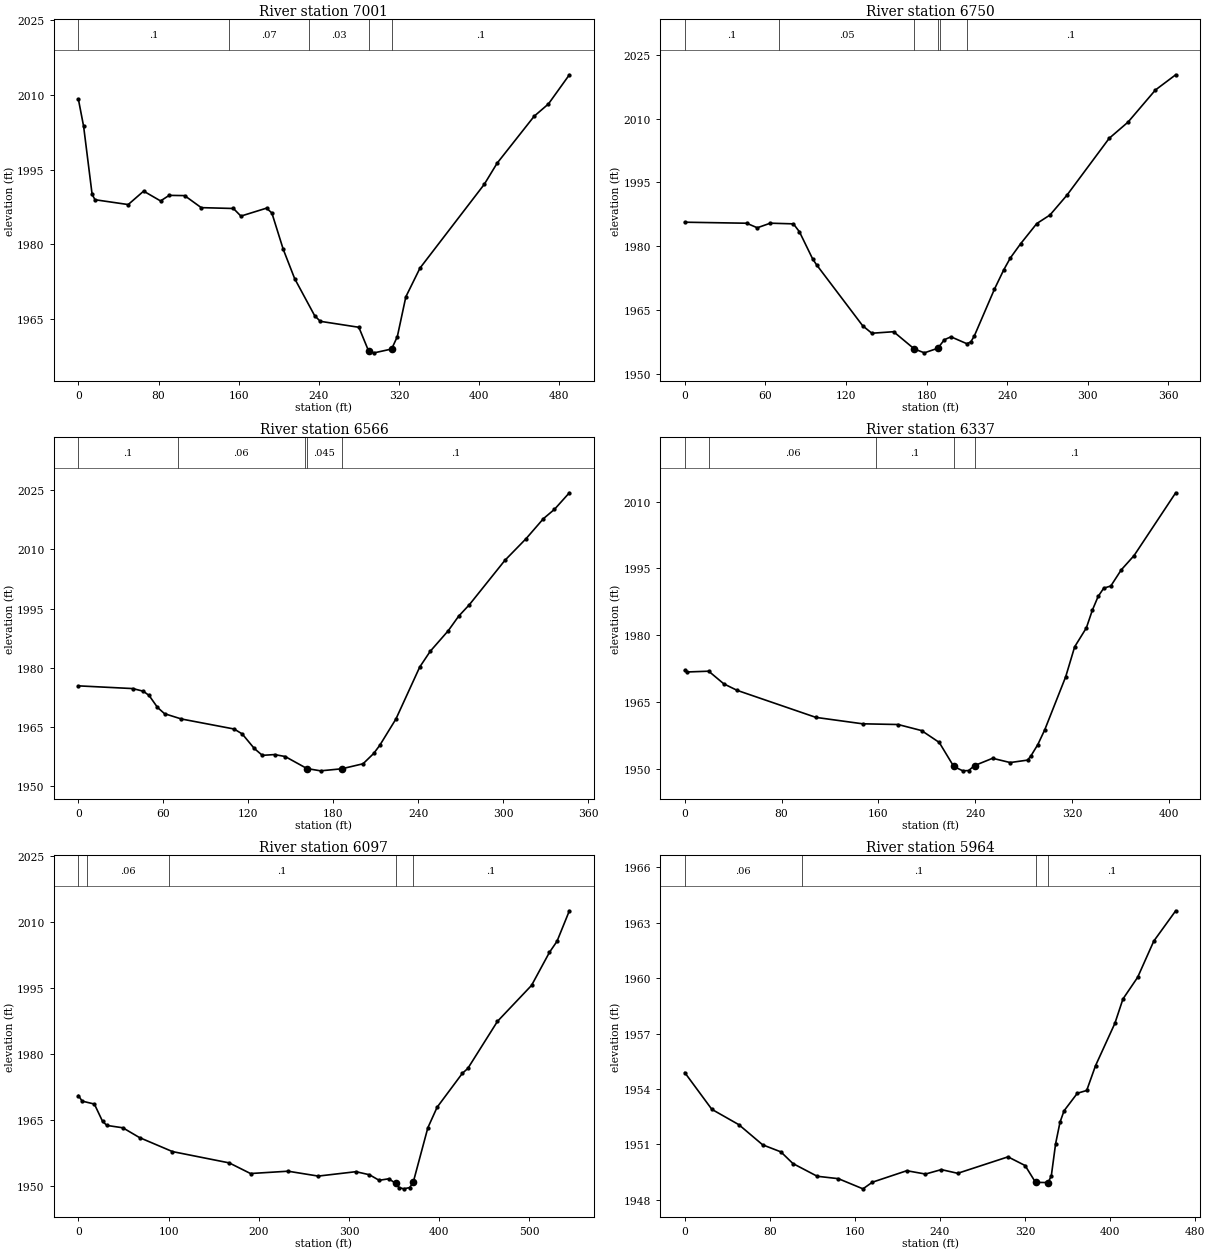
Type RM Length L Ch R = 1 ,7001    ,250.5,250.4,249.1
XS GIS Cut Line= 2
2220907.77492541687144.0715036172221213.06847783686760.827390994
#Sta/Elev= 30
       0 2009.13     5.2  2003.7    13.7 1989.99    16.6 1988.93    49.7 1987.96
    65.1 1990.66      82 1988.69    90.6 1989.81     106 1989.76   122.6 1987.34
   154.7 1987.17   162.2 1985.64   187.8 1987.24   193.1 1986.26   204.4 1978.98
   215.8 1973.08   235.8 1965.61   241.4 1964.48   279.9 1963.28   289.8 1958.43
   295.2 1958.14   312.6 1958.91   318.3  1961.4   326.8 1969.41   340.9 1975.18
   405.1 1992.04   417.9 1996.28   454.9 2005.73   469.1 2008.19     490 2014.06
#Mann= 5 ,-1,0
       0      .1       0     150     .07       0     230     .03       0
   289.8    .045       0   312.6      .1       0
Bank Sta=289.8,312.6
XS Rating Curve= 0 ,0
Exp/Cntr(USF)=0,0
Exp/Cntr=0.3,0.1

Type RM Length L Ch R = 1 ,6750    ,180.4,184,182.9
XS GIS Cut Line= 2
 2221176.9021724687218.7347728322221388.76184046686920.840721792
#Sta/Elev= 30
       0 1985.64    46.1  1985.4      54 1984.33    63.7 1985.41    80.9 1985.25
    85.4 1983.38    95.2 1977.02    98.1 1975.64   132.5 1961.27   139.3 1959.52
   155.5 1959.88   170.91955.821   178.4 1954.91   188.4 1955.99   193.3    1958
   198.2 1958.68     210 1957.06     213 1957.48   215.7 1958.97   230.6 1969.91
   237.5 1974.44   242.4 1977.23   250.1 1980.59   262.1 1985.33   271.9 1987.33
   284.6 1992.02     316 2005.38     330 2009.18   350.4 2016.74   365.5 2020.32
#Mann= 6 ,-1,0
       0      .1       0      70     .05       0   170.9    .045       0
   188.4     .05       0     190     .08       0     210      .1       0
Bank Sta=170.9,188.4
XS Rating Curve= 0 ,0
Exp/Cntr(USF)=0,0
Exp/Cntr=0.3,0.1

Type RM Length L Ch R = 1 ,6566    ,227.9,229.3,227
XS GIS Cut Line= 2
2221318.97027196687309.7869001692221527.16272445687032.777695596
#Sta/Elev= 30
       0 1975.43    38.4 1974.74    45.8 1974.07    49.9 1972.99    55.8 1969.98
    60.8 1968.38    72.7 1967.04   109.9  1964.5   115.6 1963.26   124.1 1959.59
   129.8 1957.83   138.4 1958.03   145.9 1957.54   161.3 1954.49   170.9 1953.91
   185.9 1954.43   200.9  1955.7   208.4 1958.31   212.7 1960.38   224.1 1967.04
   240.9  1980.2   248.3 1984.18     261 1989.38   268.3 1993.04     276 1996.01
     301 2007.21     316 2012.72   328.2 2017.77     336 2020.13   346.5 2024.32
#Mann= 5 ,-1,0
       0      .1       0      70     .06       0     160     .07       0
   161.3    .045       0   185.9      .1       0
Bank Sta=161.3,185.9
XS Rating Curve= 0 ,0
Exp/Cntr(USF)=0,0
Exp/Cntr=0.3,0.1

Type RM Length L Ch R = 1 ,6337    ,233.9,239.7,241.5
XS GIS Cut Line= 4
2221454.68534712687472.8759292452221555.34557519687364.472606701
 2221670.5241054687197.9960756512221703.43225688687153.473282463
#Sta/Elev= 30
       0 1972.14     2.2 1971.75    19.8 1971.92    32.3 1969.08    43.3 1967.62
   108.4 1961.55     147 1960.11   176.3 1959.95   195.7 1958.59   210.3 1955.93
   222.3 1950.53   229.8 1949.55   234.6 1949.62   239.5 1950.73   254.4 1952.37
   268.9 1951.41   283.3 1951.96     286 1952.87   291.8 1955.46   297.5 1958.77
   314.8 1970.67   322.2 1977.39   331.9 1981.66   336.8  1985.6   341.6  1988.7
   346.2 1990.55   352.1 1991.06   360.7 1994.67   371.3 1997.88   405.7 2011.98
#Mann= 5 ,-1,0
       0      .1       0      20     .06       0  157.93      .1       0
   222.3    .045       0   239.5      .1       0
Bank Sta=222.3,239.5
XS Rating Curve= 0 ,0
Exp/Cntr(USF)=0,0
Exp/Cntr=0.3,0.1

Type RM Length L Ch R = 1 ,6097    ,126.8,133.5,138.7
XS GIS Cut Line= 4
 2221508.6174871687560.4876092372221742.29111986687433.029264094
2221853.81717186687332.1247408562221941.44478415687239.186364189
#Sta/Elev= 30
       0 1970.49     4.1 1969.22    17.7 1968.55    26.8 1964.61    31.6 1963.69
    49.3 1963.15    67.8 1960.92   104.3 1957.74   167.2 1955.17   190.8 1952.75
   232.4 1953.28   265.9 1952.17   307.7 1953.17   322.7 1952.47   333.4 1951.21
   344.2 1951.56   351.6 1950.51   355.4 1949.56   360.9 1949.27   367.3 1949.57
   371.2 1950.76   387.4 1963.15   397.7 1967.83   425.8 1975.57   431.7 1976.64
   464.6 1987.36   502.4 1995.54   522.2 2003.04   530.6 2005.56   544.3  2012.5
#Mann= 5 ,-1,0
       0      .1       0      10     .06       0     100      .1       0
   351.6    .045       0   371.2      .1       0
Bank Sta=351.6,371.2
XS Rating Curve= 0 ,0
Exp/Cntr(USF)=0,0
Exp/Cntr=0.3,0.1

Type RM Length L Ch R = 1 ,5964    ,164,41.3,40.5
XS GIS Cut Line= 6
 2221641.3769479687645.2817215652221736.05830082687524.299992829
2221828.10961616687471.6992412042221888.60048053687464.685807654
2221944.70794893687452.4122989422222021.85571798687419.975168774
#Sta/Elev= 30
       0 1954.89    25.5  1952.9    50.9 1952.07    73.3 1950.98    90.4  1950.6
   101.7 1949.97   124.6 1949.28   144.5 1949.15   167.6  1948.6   176.5 1948.96
   208.8 1949.58   226.4  1949.4   241.3 1949.64   256.7 1949.44     304 1950.33
   320.1 1949.86   329.9 1948.95   341.6 1948.94   344.7 1949.29   348.8 1951.05
   352.9  1952.2   356.7 1952.82   369.2 1953.77     378 1953.92   386.3 1955.26
   404.5 1957.55   412.1 1958.87   425.9 1960.04   441.1    1962   461.7 1963.64
#Mann= 4 ,-1,0
       0     .06       0     110      .1       0   329.9    .045       0
   341.6      .1       0
Bank Sta=329.9,341.6
XS Rating Curve= 0 ,0
Exp/Cntr(USF)=0,0
Exp/Cntr=0.3,0.1

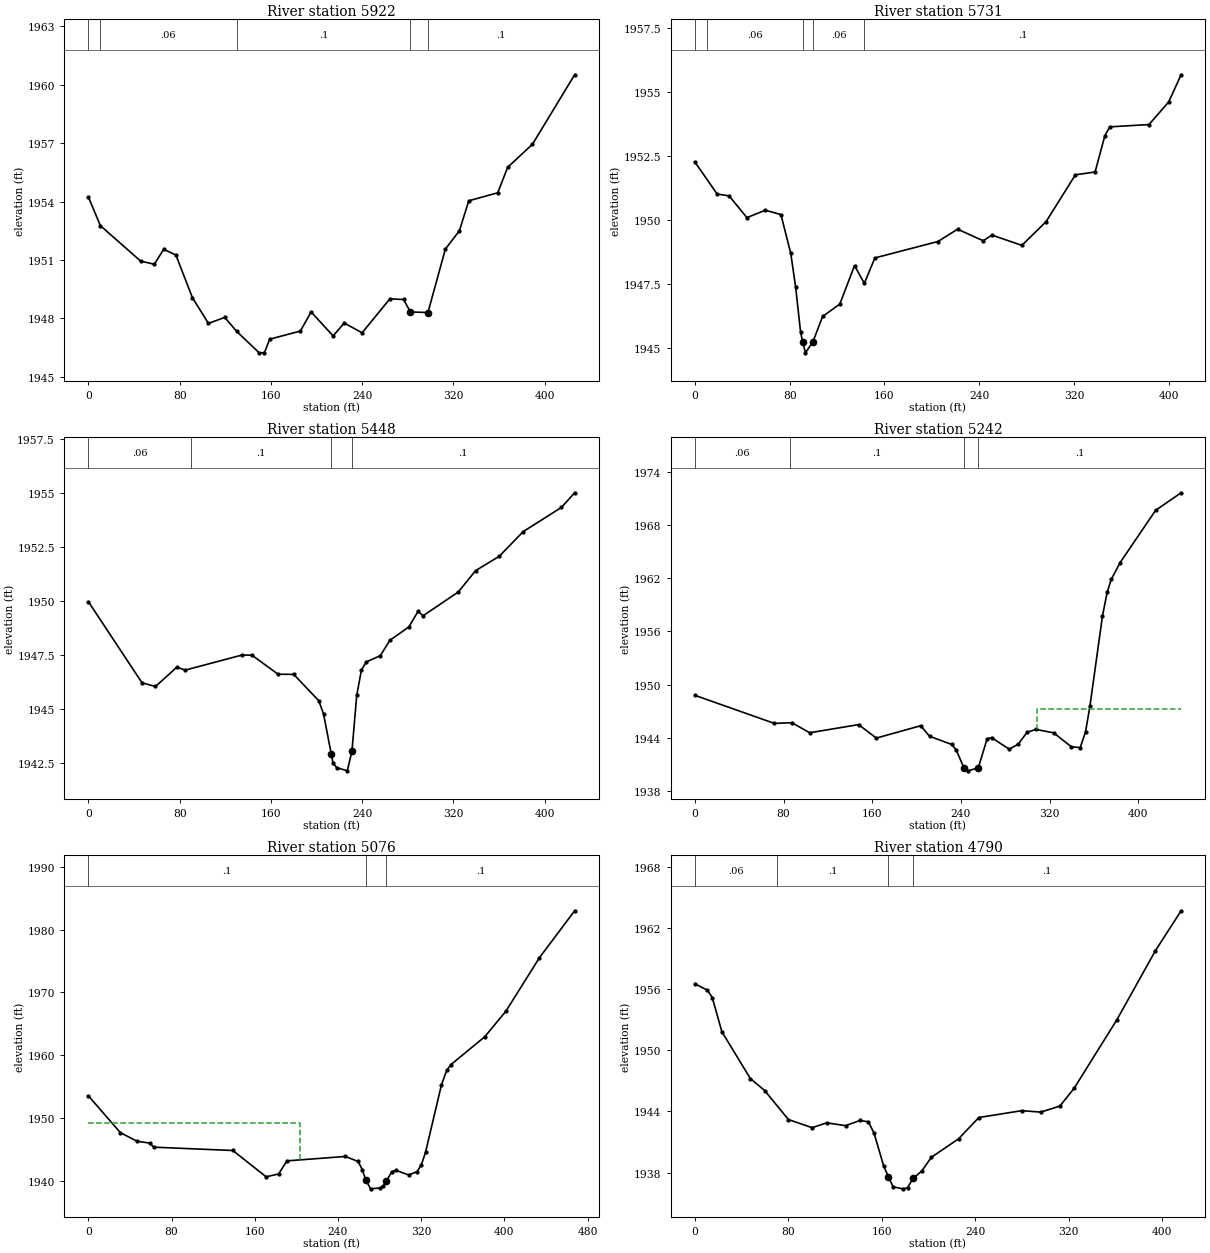
Type RM Length L Ch R = 1 ,5922    ,64.9,191.2,184.8
XS GIS Cut Line= 6
2221672.93739887687661.5002866492221754.46856389687555.422104207
2221832.49301213687509.834786132 2221892.9838765687502.821352582
 2221949.0913449 687490.547843872222026.23911395687458.110713701
#Sta/Elev= 30
       0 1954.23    10.5 1952.76    45.8 1950.94    57.8 1950.78      66 1951.55
    76.7 1951.25    91.2 1949.06   105.2 1947.74   119.5 1948.05     130 1947.33
   149.7 1946.23   154.3 1946.24   158.9 1946.93   185.8 1947.35   195.2 1948.33
   214.5  1947.1   224.2 1947.76   239.9 1947.26   264.2    1949   276.2 1948.97
   282.2 1948.34   282.3 1948.33   297.6  1948.3   312.9 1951.56   325.2  1952.5
   333.4 1954.04   358.8 1954.45   367.5 1955.76   389.2 1956.94   426.2 1960.51
#Mann= 5 ,-1,0
       0      .1       0      10     .06       0     130      .1       0
   282.2    .045       0   297.6      .1       0
Bank Sta=282.3,297.6
XS Rating Curve= 0 ,0
Exp/Cntr(USF)=0,0
Exp/Cntr=0.3,0.1

Type RM Length L Ch R = 1 ,5731    ,279.4,283.4,279.7
XS GIS Cut Line= 3
2221684.33422839687660.1852678582221728.16818808687602.324441071
2222054.29284815687514.656521697
#Sta/Elev= 30
       0 1952.26    18.8 1951.01    28.9 1950.94    43.9 1950.09    59.4 1950.38
    72.6 1950.21    80.9  1948.7      85 1947.39    89.2 1945.63      911945.234
    93.3 1944.82    99.6 1945.25   107.8 1946.24   122.3 1946.72   134.7 1948.22
     143 1947.53   151.9 1948.52   205.1 1949.16   221.7 1949.64   243.3 1949.19
   250.7 1949.41   275.9 1949.01   296.3 1949.93   321.1 1951.76   337.7 1951.87
     346 1953.29   350.1 1953.63   383.2 1953.72   399.8  1954.6   410.3 1955.66
#Mann= 5 ,-1,0
       0      .1       0      10     .06       0      91    .045       0
    99.6     .06       0  142.59      .1       0
Bank Sta=91,99.6
XS Rating Curve= 0 ,0
Exp/Cntr(USF)=0,0
Exp/Cntr=0.3,0.1

Type RM Length L Ch R = 1 ,5448    ,202,206.1,208.3
XS GIS Cut Line= 4
2221722.97301034687789.1298859022221857.59948376 687684.98487816
2221962.37952204 687655.773473552222103.35630081687613.226427704
#Sta/Elev= 30
       0 1949.98      47 1946.22    58.8 1946.05    77.4 1946.94    84.9 1946.81
   134.8 1947.51   143.4  1947.5   166.2 1946.62     180 1946.61   201.9 1945.39
   206.1 1944.78   212.91942.909   214.4  1942.5   217.6 1942.29   226.9 1942.14
     231 1943.05   235.2 1945.64   239.3 1946.81   243.6 1947.19   255.9 1947.48
   264.2 1948.19   280.9 1948.81   288.9 1949.53   293.4 1949.33   324.2 1950.43
   339.4 1951.42   360.2 1952.09   381.1 1953.23   414.6 1954.35   426.2 1955.03
#Mann= 4 ,-1,0
       0     .06       0      90      .1       0   212.9    .045       0
     231      .1       0
Bank Sta=212.9,231
XS Rating Curve= 0 ,0
Exp/Cntr(USF)=0,0
Exp/Cntr=0.3,0.1

Type RM Length L Ch R = 1 ,5242    ,158,165.5,162.7
XS GIS Cut Line= 3
2221704.55712482687857.713183683 2221790.0337157  687855.6955462
2222143.11069317 687848.07517978
#Sta/Elev= 30
       0  1948.8    71.6 1945.64    87.6 1945.71   103.6 1944.58   147.7  1945.5
   163.7 1943.98   203.7 1945.37   211.7 1944.19   231.7 1943.26   235.7 1942.66
   242.8 1940.62   246.7 1940.29   255.7 1940.64   263.7  1943.9   267.7 1944.03
   283.7 1942.73   291.7 1943.29   299.7 1944.63   307.7 1944.96   323.7 1944.57
   339.7    1943   347.7 1942.91   352.5  1944.7   356.4 1947.56   367.7 1957.69
     372 1960.42   375.7 1961.86   383.6 1963.74   415.7 1969.64   438.7 1971.62
#Mann= 4 ,-1,0
       0     .06       0    85.5      .1       0   242.8    .045       0
   255.7      .1       0
#XS Ineff= 2 , 0
                          308.45         1947.29
Permanent Ineff=
       F       F
Bank Sta=242.8,255.7
XS Rating Curve= 0 ,0
Exp/Cntr(USF)=0,0
Exp/Cntr=0.3,0.1

Type RM Length L Ch R = 1 ,5076    ,282.5,286.4,283.9
XS GIS Cut Line= 3
2221661.30448949687964.7415262272221891.89673978687967.659325397
2222125.44685877688007.877925947
#Sta/Elev= 30
       0 1953.53    30.8 1947.67    46.9 1946.31    58.9 1946.02    62.9 1945.37
   138.9 1944.84   170.9 1940.66   182.9  1941.1   190.9 1943.19   247.1 1943.89
   259.3  1943.1   263.4 1941.81   266.8 1940.08   271.5 1938.74   280.6 1938.88
   283.7 1939.15   286.51939.982   291.8 1941.45   295.8 1941.68     308 1940.95
   316.1 1941.48   320.2 1942.58   324.2 1944.54   339.5 1955.28   344.5 1957.57
   348.6  1958.5   381.1 1962.93   401.4 1966.98   433.8 1975.53   467.6 1982.98
#Mann= 3 ,-1,0
       0      .1       0   266.8    .045       0   286.5      .1       0
#XS Ineff= 2 , 0
          203.38 1949.15
Permanent Ineff=
       F       F
Bank Sta=266.8,286.5
XS Rating Curve= 0 ,0
Exp/Cntr(USF)=0,0
Exp/Cntr=0.3,0.1

Type RM Length L Ch R = 1 ,4790    ,119.3,119.4,119.6
XS GIS Cut Line= 2
2221629.55768802688116.3585718932222038.01560005 688197.10936832
#Sta/Elev= 30
       0 1956.52    10.8 1955.88    14.9 1955.17    23.1 1951.82    47.5 1947.23
    59.8 1946.05    80.1 1943.21   100.5 1942.41   112.8 1942.89   129.1 1942.61
   141.3 1943.12   148.6 1942.99   153.5 1941.86   161.7 1938.65   165.8 1937.59
   169.8 1936.62     178 1936.42   182.1 1936.52   186.8 1937.44   194.3 1938.16
   202.5 1939.51   225.9 1941.33   243.2 1943.41   279.9 1944.08   296.2 1943.94
   312.6 1944.53   324.8 1946.28   361.5 1953.01   394.4 1959.76   416.4 1963.67
#Mann= 4 ,-1,0
       0     .06       0      70      .1       0   165.8    .045       0
   186.8      .1       0
Bank Sta=165.8,186.8
XS Rating Curve= 0 ,0
Exp/Cntr(USF)=0,0
Exp/Cntr=0.3,0.1