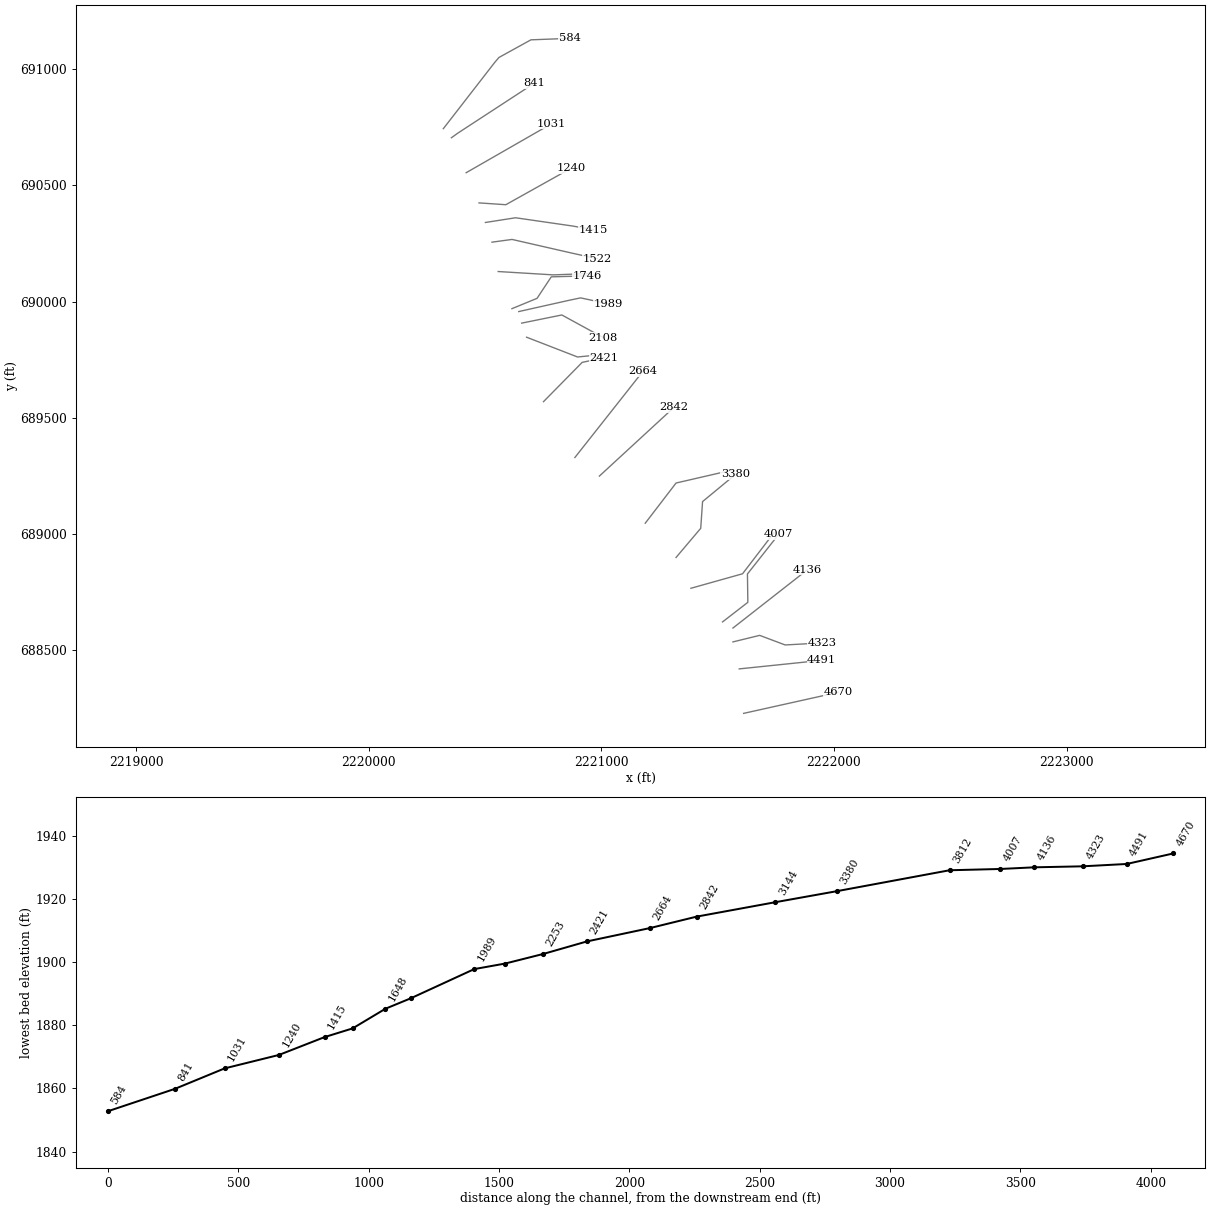
HEC-RAS study OSBORNERN.prj: OSBORNERN

--- OSBORNERN.g01 (geometry) --- (continued)

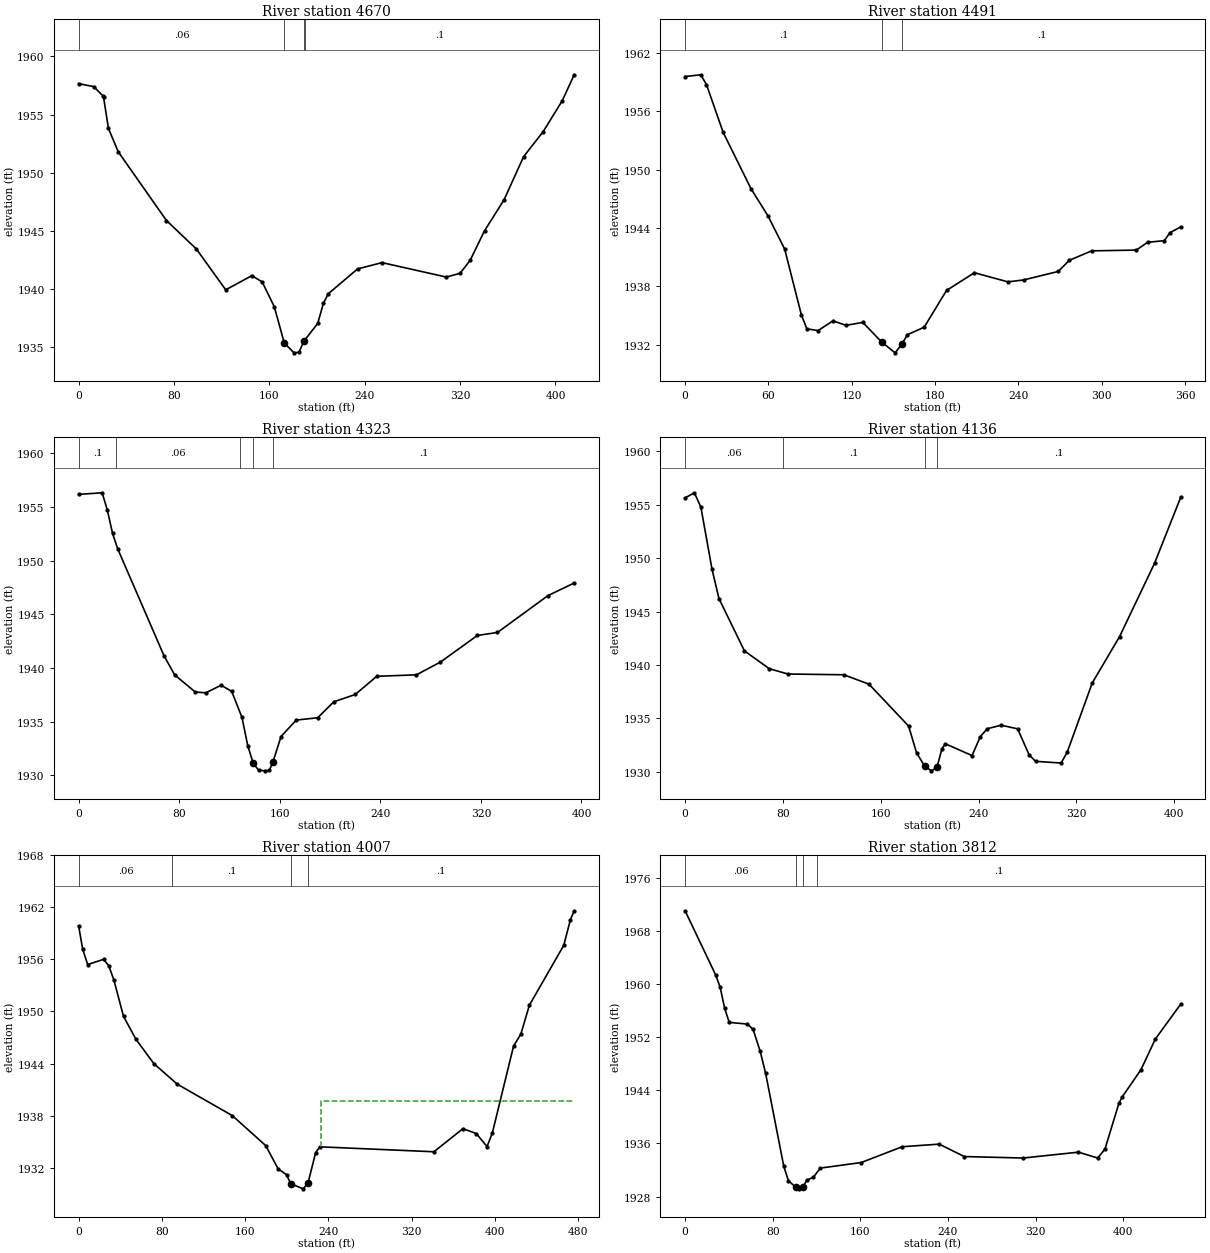
Type RM Length L Ch R = 1 ,4670    ,180.6,179.2,177.9
XS GIS Cut Line= 2
2221611.76687209688229.6139634092222017.54566928 688319.90500091
#Sta/Elev= 30
       0 1957.66    12.7  1957.4    20.1 1956.63    20.9  1956.5      25 1953.81
    33.2  1951.8    73.7 1945.88    98.8 1943.43   123.4 1939.92   145.3 1941.14
     154  1940.6   164.2 1938.45   172.5 1935.35   180.7  1934.5   184.8 1934.55
   188.9 1935.49   200.6 1937.04   205.3 1938.75   209.4 1939.58     234 1941.72
   254.5 1942.26   308.4 1941.02     320 1941.34   328.5 1942.47   340.5    1945
   356.9 1947.67   373.3 1951.38   389.7 1953.53   405.6 1956.17   415.7 1958.42
#Mann= 4 ,-1,0
       0     .06       0   172.5    .045       0   188.9     .06       0
     190      .1       0
Bank Sta=172.5,188.9
XS Rating Curve= 0 ,0
Exp/Cntr(USF)=0,0
Exp/Cntr=0.3,0.1

Type RM Length L Ch R = 1 ,4491    ,171.4,168.4,160.9
XS GIS Cut Line= 3
2221592.90125519688420.8297149692221865.25879576688449.053294303
2221947.81276531688458.225957586
#Sta/Elev= 30
       0 1959.57    11.3 1959.75    15.4 1958.74    27.4 1953.83    47.5 1948.02
    59.6 1945.26    71.7 1941.83    83.7 1935.08    87.7 1933.62    95.8 1933.44
   106.5 1934.44   115.9 1933.98     128 1934.28   141.8 1932.23   151.3 1931.15
   156.3 1932.09   160.1 1933.01   172.2 1933.79   188.3 1937.57   208.4 1939.39
   232.5 1938.45   243.8 1938.65   268.7 1939.52   276.8 1940.67   292.8 1941.64
     325 1941.72   333.1 1942.52   345.2 1942.69   349.2 1943.51   356.9  1944.1
#Mann= 3 ,-1,0
       0      .1       0   141.8    .045       0   156.3      .1       0
Bank Sta=141.8,156.3
XS Rating Curve= 0 ,0
Exp/Cntr(USF)=0,0
Exp/Cntr=0.3,0.1

Type RM Length L Ch R = 1 ,4323    ,167.5,186.7,193
XS GIS Cut Line= 4
2221565.98253723688536.8644615992221680.82751161688564.918195799
2221790.41241083688523.714273693 2221949.0913449 688532.48106563
#Sta/Elev= 30
       0 1956.18    18.7 1956.33    22.8 1954.73      27 1952.54    31.1  1951.1
    67.9 1941.14    76.4 1939.35    92.8 1937.76   101.1 1937.68   113.4 1938.39
   121.8 1937.81   129.9  1935.4   134.6 1932.73   138.9  1931.1   143.2 1930.47
   148.6 1930.41   151.7 1930.47   154.51931.202     161 1933.61   173.1 1935.14
   190.2 1935.36     203 1936.85   220.1 1937.53   237.1 1939.22   268.7 1939.36
   287.7 1940.54   317.2 1943.03   333.2 1943.31   373.3 1946.74   394.2 1947.92
#Mann= 5 ,-1,0
       0      .1       0      30     .06       0  128.22      .1       0
   138.9    .045       0   154.5      .1       0
Bank Sta=138.9,154.5
XS Rating Curve= 0 ,0
Exp/Cntr(USF)=0,0
Exp/Cntr=0.3,0.1

Type RM Length L Ch R = 1 ,4136    ,89.5,129.2,117
XS GIS Cut Line= 2
2221565.98253724688596.4786467742221885.09376376 688846.33221699
#Sta/Elev= 30
       0 1955.63     7.6 1956.11    12.9 1954.77      22 1948.97    27.7 1946.21
    48.5 1941.32    68.8 1939.65    84.1 1939.15   129.8 1939.08   150.4  1938.2
   182.8 1934.28   189.3 1931.78     196 1930.52   201.5 1930.09     206 1930.42
   210.1 1932.17   212.9 1932.62   234.7 1931.52   241.4 1933.28   247.1 1934.03
   258.5 1934.36     272 1934.02   281.3  1931.6   286.6 1930.98   307.6 1930.82
   312.6 1931.86     333 1938.31   355.4 1942.66     384 1949.52   405.3 1955.67
#Mann= 4 ,-1,0
       0     .06       0      80      .1       0     196    .045       0
     206      .1       0
Bank Sta=196,206
XS Rating Curve= 0 ,0
Exp/Cntr(USF)=0,0
Exp/Cntr=0.3,0.1

Type RM Length L Ch R = 1 ,4007    ,208.8,195.3,181.8
XS GIS Cut Line= 4
2221521.27189835688622.7790225862221629.98011838688706.940225185
2221628.22675999688828.7986331152221762.35867663  688998.8743967
#Sta/Elev= 30
       0 1959.86     3.9 1957.16     8.7 1955.41    23.9    1956      29 1955.26
      34 1953.57    43.1 1949.44    55.1 1946.79    72.2    1944    94.7 1941.63
   147.7    1938   179.7 1934.55   191.7 1931.86   199.7  1931.2   203.7 1930.16
   215.7 1929.57   220.3 1930.22   227.7 1933.75   231.7 1934.41   341.3 1933.84
   369.1  1936.5     382 1935.94   392.3 1934.44   397.4 1936.01   417.8 1946.02
   424.8  1947.4     433 1950.73     466 1957.62   472.4 1960.58     476  1961.6
#Mann= 4 ,-1,0
       0     .06       0      90      .1       0   203.7    .045       0
   220.3      .1       0
#XS Ineff= 2 , 0
                          232.39         1939.64
Permanent Ineff=
       F       F
Bank Sta=203.7,220.3
XS Rating Curve= 0 ,0
Exp/Cntr(USF)=0,0
Exp/Cntr=0.3,0.1

Type RM Length L Ch R = 1 ,3812    ,416.6,432.2,448.3
XS GIS Cut Line= 3
2221385.38662332688767.4310895532221607.18645934688829.675312308
2221742.19505518 689005.88783025
#Sta/Elev= 30
       0 1971.02    27.8  1961.4      32 1959.52    36.1 1956.34    40.3 1954.22
    56.9 1953.96    62.1 1953.16    68.6 1949.84    73.5 1946.56    90.1 1932.55
    94.3  1930.4     101  1929.4   104.2 1929.16   107.5 1929.38   110.9 1930.44
   117.2 1930.92   123.4 1932.28   160.8 1933.12   198.2  1935.5     232 1935.89
   254.9 1934.02   308.6  1933.8   359.1 1934.68   376.7  1933.8   383.3 1935.14
     396 1942.02   399.1 1943.01   416.2  1947.1   429.3 1951.71   452.4 1956.95
#Mann= 4 ,-1,0
       0     .06       0     101    .045       0   107.5     .06       0
     120      .1       0
Bank Sta=101,107.5
XS Rating Curve= 0 ,0
Exp/Cntr(USF)=0,0
Exp/Cntr=0.3,0.1

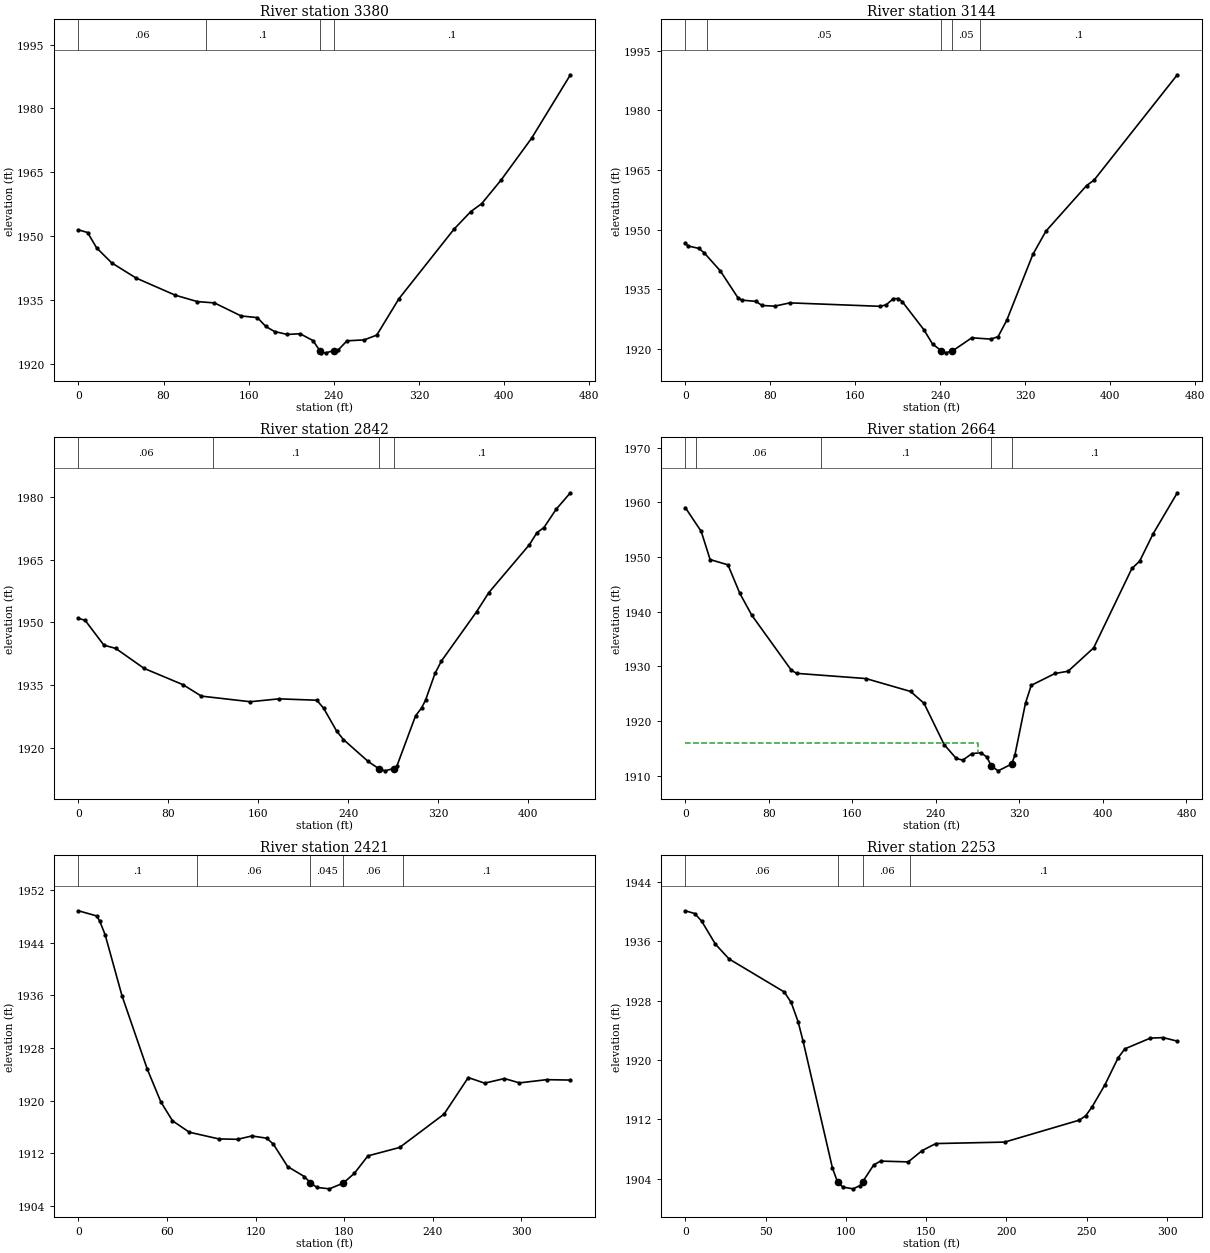
Type RM Length L Ch R = 1 ,3380    ,251.3,235.6,216.8
XS GIS Cut Line= 4
2221321.38904218688899.8096478082221427.46722462689025.174772513
2221435.35733737689140.0197468932221576.50268756 689256.61807966
#Sta/Elev= 30
       0 1951.44     8.6 1950.81    17.1 1947.19    31.3 1943.67    54.2 1940.11
      91 1936.08   111.8 1934.57   127.8 1934.27   152.9  1931.2   168.2 1930.81
   176.1 1928.73   184.3 1927.54   196.3 1926.85   208.3 1927.02   220.4 1925.42
     2271922.998   228.4 1922.57   232.4 1922.53   239.9 1923.04   244.4 1923.27
   252.4 1925.36   268.5 1925.57   280.4  1926.7   301.2 1935.24     353  1951.6
   368.8 1955.74     379  1957.6   397.2 1963.13     426    1973   462.4 1987.89
#Mann= 4 ,-1,0
       0     .06       0     120      .1       0     227    .045       0
   239.9      .1       0
Bank Sta=227,239.9
XS Rating Curve= 0 ,0
Exp/Cntr(USF)=0,0
Exp/Cntr=0.3,0.1

Type RM Length L Ch R = 1 ,3144    ,292.1,301.8,307.8
XS GIS Cut Line= 3
2221189.01048393689047.0917523562221321.38904218689219.797553523
2221560.72246207689275.028342728
#Sta/Elev= 30
       0 1946.57     2.6 1945.89    12.7 1945.29    17.7 1944.18    32.9 1939.64
    49.4 1932.93      53 1932.29    66.5 1931.97    72.2 1930.94    84.1 1930.77
    98.4  1931.6   183.5 1930.73   189.1 1931.12   195.9 1932.67   200.6 1932.68
   204.2 1931.92   224.6 1924.84   232.8 1921.23     241 1919.57   245.1 1919.04
   251.5 1919.51   269.7 1922.82   287.8 1922.49   294.5 1923.12   302.6 1927.22
   327.2 1943.78   339.5 1949.62   377.8 1961.09   384.7 1962.41   463.2 1988.92
#Mann= 5 ,-1,0
       0     .06       0      20     .05       0     241    .045       0
   251.5     .05       0   277.6      .1       0
Bank Sta=241,251.5
XS Rating Curve= 0 ,0
Exp/Cntr(USF)=0,0
Exp/Cntr=0.3,0.1

Type RM Length L Ch R = 1 ,2842    ,176,178.2,180.5
XS GIS Cut Line= 2
2220991.75766533 689249.604646112221313.49892944689545.922213594
#Sta/Elev= 30
       0 1950.96       6 1950.45    22.6 1944.54    33.2 1943.74    58.4 1938.97
      93 1935.07   109.3 1932.34   152.8    1931   178.3 1931.69   211.9 1931.36
     218 1929.45   229.6 1923.96   235.6 1921.96   257.6 1916.71     267 1914.99
   272.5 1914.47   280.2 1915.02   283.1 1915.59   299.7 1927.61   305.1 1929.52
   308.6 1931.38     317 1937.76   322.7 1940.73     354 1952.53   364.9 1957.12
   400.9 1968.55   407.6 1971.41   413.9 1972.67   424.7 1977.03   437.4 1980.98
#Mann= 4 ,-1,0
       0     .06       0     120      .1       0     267    .045       0
   280.2      .1       0
Bank Sta=267,280.2
XS Rating Curve= 0 ,0
Exp/Cntr(USF)=0,0
Exp/Cntr=0.3,0.1

Type RM Length L Ch R = 1 ,2664    ,243.7,243.1,239.5
XS GIS Cut Line= 2
2220886.52178439689329.4830630072221178.54222805689699.322567298
#Sta/Elev= 30
       0 1959.03    15.2 1954.68    23.7 1949.53    40.8 1948.56    52.2 1943.33
    63.6 1939.35   101.5 1929.28   106.6  1928.7   172.9 1927.75   215.7 1925.39
   228.6 1923.22   247.9 1915.66   259.5 1913.12   265.8 1912.82   274.4 1914.01
   282.9 1914.17   288.6 1913.42   293.1 1911.74   299.6 1910.86   312.5  1912.1
   315.6 1913.72   325.8 1923.26   331.3 1926.51   354.1 1928.68   366.6 1929.09
   391.1 1933.37   427.7  1947.9   435.1 1949.22   448.1 1954.27   471.2 1961.75
#Mann= 5 ,-1,0
       0      .1       0      10     .06       0     130      .1       0
   293.1    .045       0   312.5      .1       0
#XS Ineff= 2 , 0
          280.19 1915.92
Permanent Ineff=
       F       F
Bank Sta=293.1,312.5
XS Rating Curve= 0 ,0
Exp/Cntr(USF)=0,0
Exp/Cntr=0.3,0.1

Type RM Length L Ch R = 1 ,2421    ,182.5,167.6,148.4
XS GIS Cut Line= 3
2220751.47830528 689569.421403312220917.85804764689738.414440061
2221011.93664542689758.449696995
#Sta/Elev= 30
       0 1948.88    12.4 1948.09    14.5 1947.26    18.1 1945.22    29.5 1935.96
    46.6 1924.82    55.8 1919.83    63.7 1916.95    75.1 1915.21    95.1 1914.19
   107.8 1914.13   117.5 1914.64   127.6  1914.3   132.1 1913.38   141.7 1909.99
   153.1 1908.46   157.1 1907.54   161.5 1906.82     170  1906.6   179.3 1907.46
     187 1908.97   196.1 1911.61   217.6 1912.89   247.7 1917.96   264.1 1923.52
   275.2 1922.67   288.6 1923.37   298.8 1922.71   317.2  1923.2   333.3 1923.14
#Mann= 5 ,-1,0
       0      .1       0      80     .06       0   157.1    .045       0
   179.3     .06       0     220      .1       0
Bank Sta=157.1,179.3
XS Rating Curve= 0 ,0
Exp/Cntr(USF)=0,0
Exp/Cntr=0.3,0.1

Type RM Length L Ch R = 1 ,2253    ,146.9,145.5,143.2
XS GIS Cut Line= 3
2220678.78319317689846.623177047 2220897.9529916689761.585295254
 2220968.9640063689768.598728804
#Sta/Elev= 30
       0  1940.1     5.8 1939.73    10.1 1938.72    18.7 1935.61    27.2 1933.61
    61.6 1929.16    65.9 1927.75    70.2 1925.17    73.3 1922.55    91.6 1905.44
    94.81903.539    98.1 1902.87   104.5 1902.63   108.8 1903.07   110.4 1903.57
   117.3 1905.85   121.6 1906.37   138.8 1906.26   147.5 1907.79     156 1908.73
   198.9 1908.93   245.4 1911.89   249.4 1912.49   253.4  1913.7   261.4 1916.68
   269.5 1920.27   273.7 1921.49   289.6 1922.94   297.6 1923.01   306.4 1922.53
#Mann= 4 ,-1,0
       0     .06       0    94.8    .045       0   110.4     .06       0
     140      .1       0
Bank Sta=94.8,110.4
XS Rating Curve= 0 ,0
Exp/Cntr(USF)=0,0
Exp/Cntr=0.3,0.1

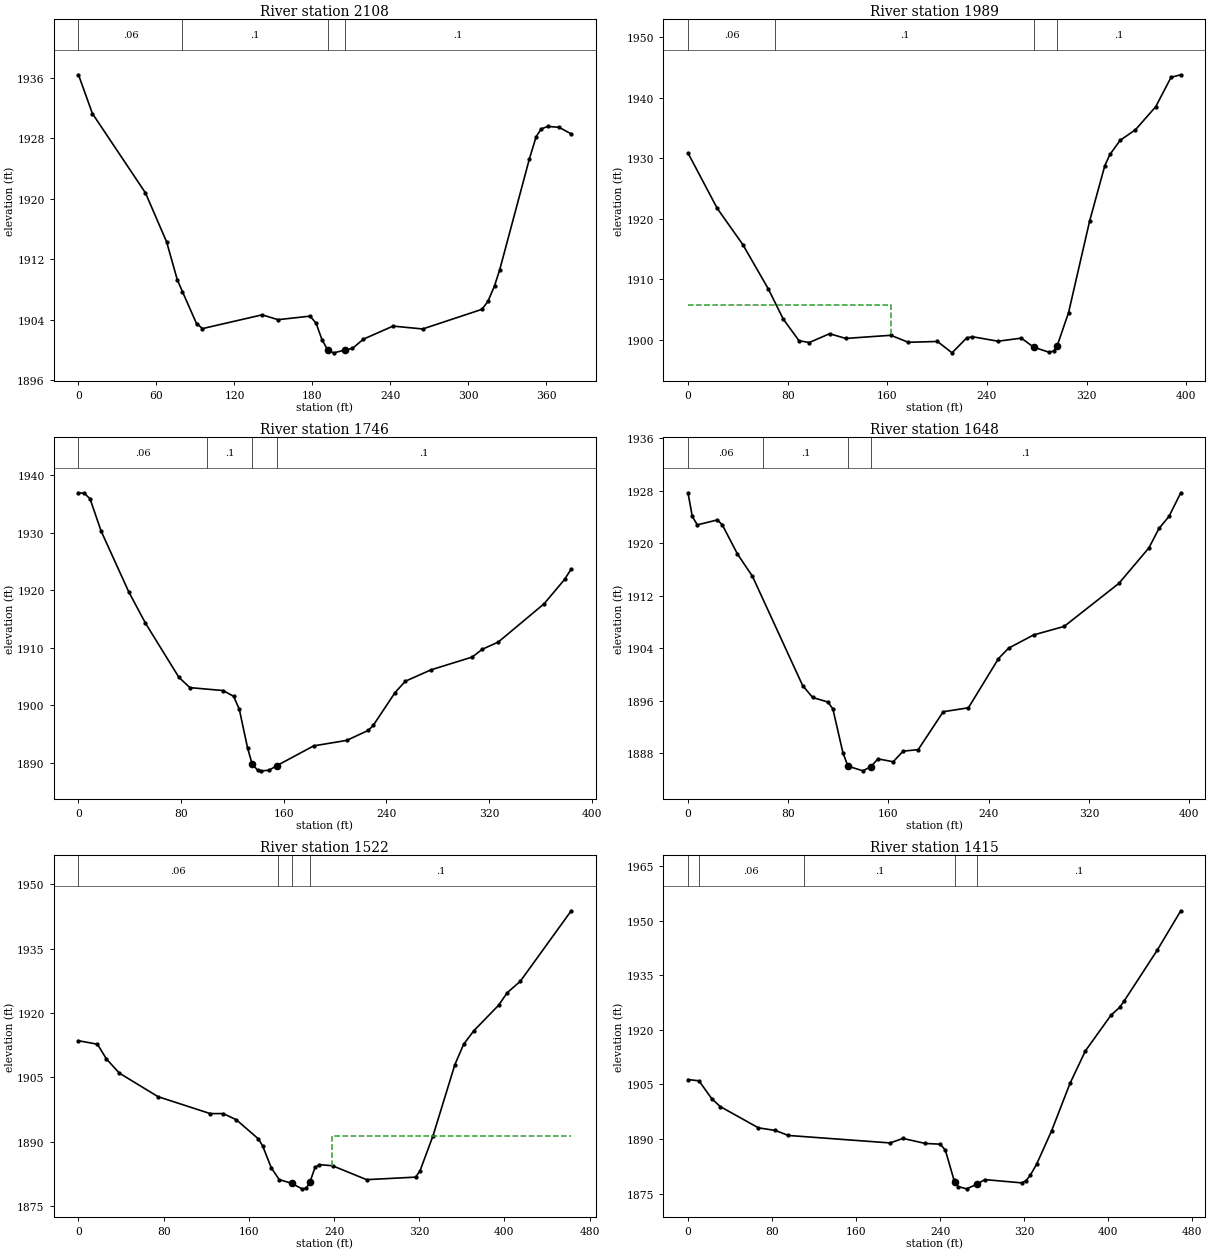
Type RM Length L Ch R = 1 ,2108    ,115.3,118.8,123.4
XS GIS Cut Line= 3
2220657.74289252689907.1140414152220830.44869369689942.181209165
2221008.41457002 689844.86981866
#Sta/Elev= 30
       0 1936.41    10.7 1931.28    51.5 1920.78    67.8 1914.29      76 1909.28
      80 1907.69    90.8 1903.48    95.4 1902.81   141.3 1904.63   153.5 1903.99
   178.2 1904.46   182.8 1903.52   187.3 1901.36   191.9 1899.91   196.4  1899.6
   204.8 1899.96   210.7 1900.18   219.2 1901.41     242 1903.14   264.8 1902.76
   310.4 1905.36     315 1906.41   320.1 1908.48   324.1 1910.62   346.9 1925.27
   352.1 1928.22     356 1929.24     361 1929.57   369.7 1929.46   379.1 1928.58
#Mann= 4 ,-1,0
       0     .06       0      80      .1       0   191.9    .045       0
   204.8      .1       0
Bank Sta=191.9,204.8
XS Rating Curve= 0 ,0
Exp/Cntr(USF)=0,0
Exp/Cntr=0.3,0.1

Type RM Length L Ch R = 1 ,1989    ,226.2,242.8,260.7
XS GIS Cut Line= 4
2220645.25674387689956.8516192112220862.42150708 690005.45889473
 2220911.0287826690015.6507428232221031.76298308689989.779128434
#Sta/Elev= 30
       0 1930.84    23.5 1921.69      44 1915.73    64.5 1908.39    76.4 1903.44
    89.1 1899.85    97.3 1899.54   113.7    1901   126.6 1900.22   162.9 1900.74
   176.9 1899.58   200.3 1899.72     212 1897.84   223.8 1900.31   228.4  1900.5
   248.9 1899.76   267.7 1900.27   277.5 1898.78   289.7 1897.95   293.8 1898.13
   296.5 1899.04   305.6  1904.5   322.5 1919.62   334.7 1928.77   338.8 1930.61
     347 1932.95   359.3  1934.7   375.6 1938.51   387.9 1943.37   395.7 1943.78
#Mann= 4 ,-1,0
       0     .06       0      70      .1       0   277.5    .045       0
   296.5      .1       0
#XS Ineff= 2 , 0
           163.1 1905.73
Permanent Ineff=
       F       F
Bank Sta=277.5,296.5
XS Rating Curve= 0 ,0
Exp/Cntr(USF)=0,0
Exp/Cntr=0.3,0.1

Type RM Length L Ch R = 1 ,1746    ,115.2,97.7,83.5
XS GIS Cut Line= 4
 2220615.8890534689969.2266982842220723.84424435690013.678835735
2220785.01502684690106.0843048622220941.38494578690110.199302729
#Sta/Elev= 30
       0 1936.93     4.6 1936.84       9 1935.88    17.6 1930.29    39.2  1919.7
    52.2 1914.27    78.2 1904.88    86.8 1903.07   112.8 1902.56   120.9 1901.55
   125.3 1899.33   131.8 1892.55   135.3 1889.82   139.7 1888.69   142.6 1888.61
   148.4 1888.71   154.5  1889.5   183.3 1892.95     209  1893.9     226 1895.66
   229.8 1896.54   246.7 1902.21   254.7 1904.18   274.7 1906.16   306.8 1908.38
   314.8 1909.75   327.2    1911   362.8 1917.63   378.8 1921.87     384 1923.69
#Mann= 4 ,-1,0
       0     .06       0     100      .1       0   135.3    .045       0
   154.5      .1       0
Bank Sta=135.3,154.5
XS Rating Curve= 0 ,0
Exp/Cntr(USF)=0,0
Exp/Cntr=0.3,0.1

Type RM Length L Ch R = 1 ,1648    ,129.8,126.1,124
XS GIS Cut Line= 3
2220556.82179834690128.9084555232220793.57998944690114.537673155
2220949.59994407 690120.28458406
#Sta/Elev= 30
       0 1927.63     3.4 1924.05     7.4 1922.77    23.4 1923.52    27.4 1922.76
    39.4 1918.34    51.4 1914.94    91.5 1898.27    99.5 1896.46   111.6 1895.77
   115.6 1894.72   123.6 1888.06   127.6    1886   139.6 1885.28     1461885.922
   151.6 1887.11   163.7 1886.66   171.7 1888.28   183.7 1888.51   203.7 1894.29
   223.8 1894.89   247.8 1902.39   255.8 1903.97   275.8 1905.99   300.2 1907.29
   343.9 1913.85   367.9 1919.27   375.9 1922.22   383.9 1924.06   393.3 1927.66
#Mann= 4 ,-1,0
       0     .06       0      60      .1       0   127.6    .045       0
     146      .1       0
Bank Sta=127.6,146
XS Rating Curve= 0 ,0
Exp/Cntr(USF)=0,0
Exp/Cntr=0.3,0.1

Type RM Length L Ch R = 1 ,1522    ,105.4,107.4,108.3
XS GIS Cut Line= 4
2220530.16619564 690255.130574212220616.40491027690266.890398932
2220873.55307753 690208.09127532   2220982.90708690184.024232114
#Sta/Elev= 30
       0 1913.56    17.8 1912.75    26.2 1909.33    38.4 1906.01    74.7 1900.52
   123.7 1896.58     136 1896.58   148.3 1895.13   168.9  1890.7     173 1889.03
   181.2 1883.87   188.5 1881.21   200.2 1880.32   209.9 1879.04     214 1879.19
   217.4 1880.65   222.2 1884.05   226.3 1884.68   238.6 1884.42   270.6 1881.18
   316.6 1881.77   320.7  1883.2     333 1891.42   353.5 1907.98   361.7 1912.72
   371.4 1915.91   394.5 1921.81   402.7 1924.76   414.9  1927.4   462.8 1943.85
#Mann= 4 ,-1,0
       0     .06       0  187.04      .1       0   200.2    .045       0
   217.4      .1       0
#XS Ineff= 2 , 0
                          238.31         1891.41
Permanent Ineff=
       F       F
Bank Sta=200.2,217.4
XS Rating Curve= 0 ,0
Exp/Cntr(USF)=0,0
Exp/Cntr=0.3,0.1

Type RM Length L Ch R = 1 ,1415    ,164.9,175.1,184.3
XS GIS Cut Line= 4
 2220501.9426163 690339.801312212220631.54753061690360.024448908
2220876.74552208690324.5352659332220965.53708224690308.566287466
#Sta/Elev= 30
       0 1906.34    10.4 1905.99    22.5 1901.11    30.6 1898.92      67 1893.06
    83.2 1892.34    95.4 1890.97   192.4 1888.91   204.6 1890.15     226 1888.76
   240.2 1888.57     245 1886.91   253.1  1878.8   254.3  1878.1   257.1 1876.92
   265.2 1876.29   275.5 1877.63   282.5 1878.83   317.7 1877.93   321.8 1878.55
   325.8 1880.01   331.8 1883.03   346.1 1892.23   363.7 1905.32   378.3 1914.22
   402.7 1924.04   410.9 1926.18   414.9 1927.81   446.8 1941.96   469.1 1952.74
#Mann= 5 ,-1,0
       0      .1       0      10     .06       0     110      .1       0
   254.3    .045       0   275.5      .1       0
Bank Sta=254.3,275.5
XS Rating Curve= 0 ,0
Exp/Cntr(USF)=0,0
Exp/Cntr=0.3,0.1

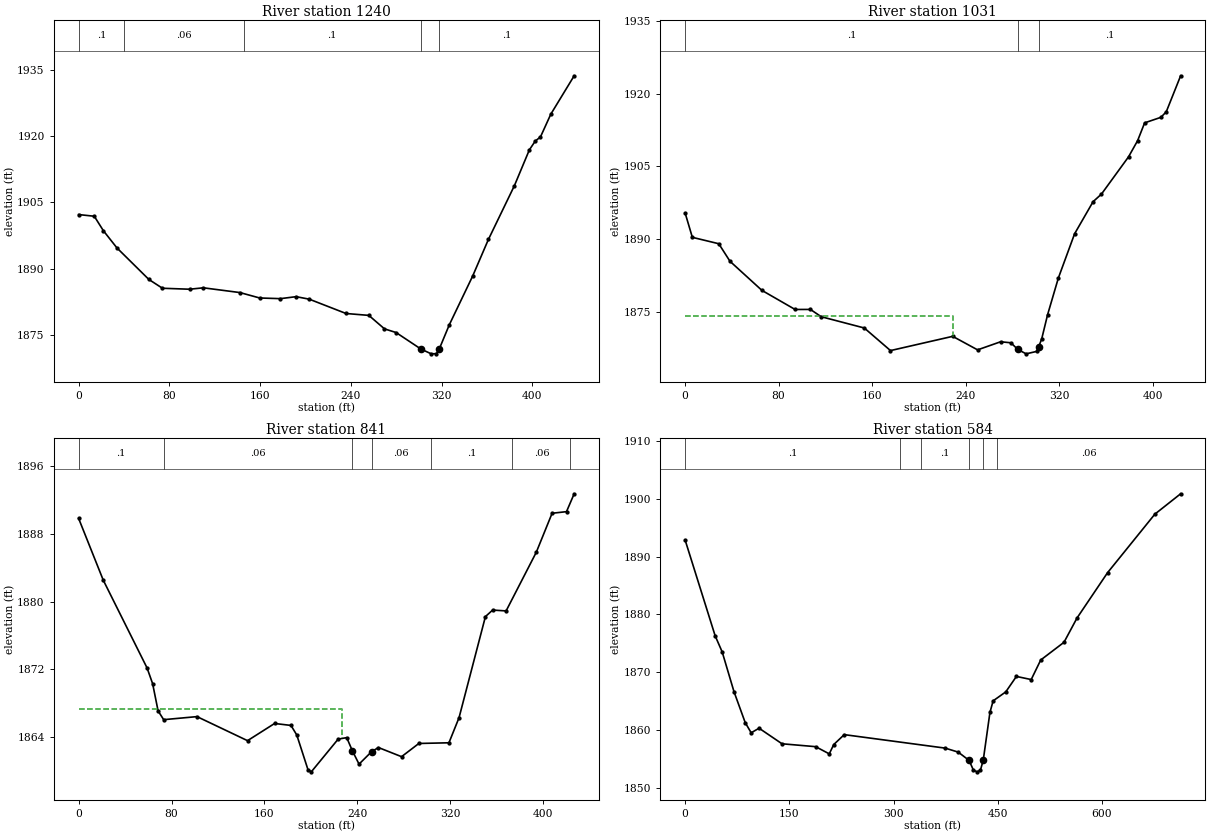
Type RM Length L Ch R = 1 ,1240    ,208.2,208.7,208.4
XS GIS Cut Line= 3
2220474.44712846690423.9584353272220589.65525288690416.121215401
2220870.14884996690572.918878368
#Sta/Elev= 30
       0 1902.25    13.8 1901.87    21.8 1898.59    33.8 1894.67    61.9 1887.52
    73.9 1885.52    97.8  1885.3     110 1885.62   142.2 1884.54   159.6 1883.31
   177.9 1883.16   191.7 1883.61   203.3 1883.04   235.7 1879.79   255.8 1879.36
   269.6  1876.3   279.8 1875.47   301.7 1871.72   310.8 1870.63   315.4 1870.67
     318 1871.81   326.8 1877.26   347.4 1888.33   361.2  1896.6   384.1  1908.8
   397.3 1916.94   402.5 1918.94   407.1 1919.88   416.2 1925.04   436.8 1933.76
#Mann= 5 ,-1,0
       0      .1       0      40     .06       0  145.47      .1       0
   301.7    .045       0     318      .1       0
Bank Sta=301.7,318
XS Rating Curve= 0 ,0
Exp/Cntr(USF)=0,0
Exp/Cntr=0.3,0.1

Type RM Length L Ch R = 1 ,1031    ,188,190.1,189.9
XS GIS Cut Line= 2
2220419.21341114 690553.702136042220786.84158056 690764.71789782
#Sta/Elev= 30
       0 1895.43     6.2 1890.39    28.8 1889.07    38.4 1885.45    65.7 1879.45
    94.1 1875.51   107.2 1875.52   116.4 1874.02   153.3 1871.69   175.7 1867.03
   228.9 1869.97   250.2 1867.18   269.9 1868.85   278.7 1868.64   284.5 1867.29
   291.7 1866.36   300.9 1866.87   302.41867.752   305.1 1869.49   310.1 1874.44
   319.3    1882   333.2 1891.13     349 1897.74   356.2 1899.32   379.3 1906.98
   387.1 1910.33   393.1    1914     407 1915.14   411.6 1916.28   423.9 1923.71
#Mann= 3 ,-1,0
       0      .1       0   284.5    .045       0   302.4      .1       0
#XS Ineff= 2 , 0
          229.58 1874.14
Permanent Ineff=
       F       F
Bank Sta=284.5,302.4
XS Rating Curve= 0 ,0
Exp/Cntr(USF)=0,0
Exp/Cntr=0.3,0.1

Type RM Length L Ch R = 1 ,841     ,252.7,257.3,253.2
XS GIS Cut Line= 3
2220355.78093809690703.9249008992220382.86026013690723.519231617
2220712.10704373690938.392240607
#Sta/Elev= 30
       0 1889.81    21.2 1882.52    58.9 1872.16    63.7  1870.3    68.4 1867.09
    73.2 1866.05   101.9 1866.41   145.4 1863.57   168.7  1865.6   182.8 1865.37
   187.8 1864.24   197.4 1860.16   200.3 1859.89   223.4 1863.75   230.8 1863.93
   235.6 1862.39   241.4  1860.8   252.2 1862.27   258.1 1862.76     278 1861.68
   292.9 1863.24   318.8 1863.32   327.5 1866.29   350.2 1878.22   356.4 1878.99
     368 1878.89     394 1885.82   407.6 1890.42     420 1890.61   426.6 1892.72
#Mann= 7 ,-1,0
       0      .1       0   73.42     .06       0   235.6    .045       0
   252.2     .06       0  303.42      .1       0  373.42     .06       0
  423.42      .1       0
#XS Ineff= 2 , 0
          227.04 1867.27
Permanent Ineff=
       F       F
Bank Sta=235.6,252.2
XS Rating Curve= 0 ,0
Exp/Cntr(USF)=0,0
Exp/Cntr=0.3,0.1

Type RM Length L Ch R = 1 ,584     ,51.2,59.3,68.5
XS GIS Cut Line= 5
2220321.00554665690742.9526465682220540.78037795691026.349904074
2220559.94453675 691048.998455392220697.52368811691124.868069902
 2220865.2907349691131.320648625
#Sta/Elev= 30
       0 1892.87    43.3 1876.29    53.4 1873.51    70.4 1866.64    86.5 1861.31
    95.1 1859.54   106.5 1860.33   139.5 1857.64   187.9 1857.14   207.5  1855.9
     214 1857.51   229.1 1859.22   374.4 1856.89   393.1  1856.2   408.8 1854.77
   415.1 1853.06   420.5 1852.79   425.1 1853.07   429.2 1854.83   438.8 1863.06
   443.4 1865.06   461.6 1866.61   476.9 1869.28   498.2 1868.74   511.9 1872.12
   545.4 1875.18   564.1 1879.37   608.1 1887.21   676.2 1897.33   713.3 1900.85
#Mann= 6 ,-1,0
       0      .1       0     310     .06       0     340      .1       0
   408.8    .045       0   429.2      .1       0   448.3     .06       0
Bank Sta=408.8,429.2
XS Rating Curve= 0 ,0
Exp/Cntr(USF)=0,0
Exp/Cntr=0.3,0.1