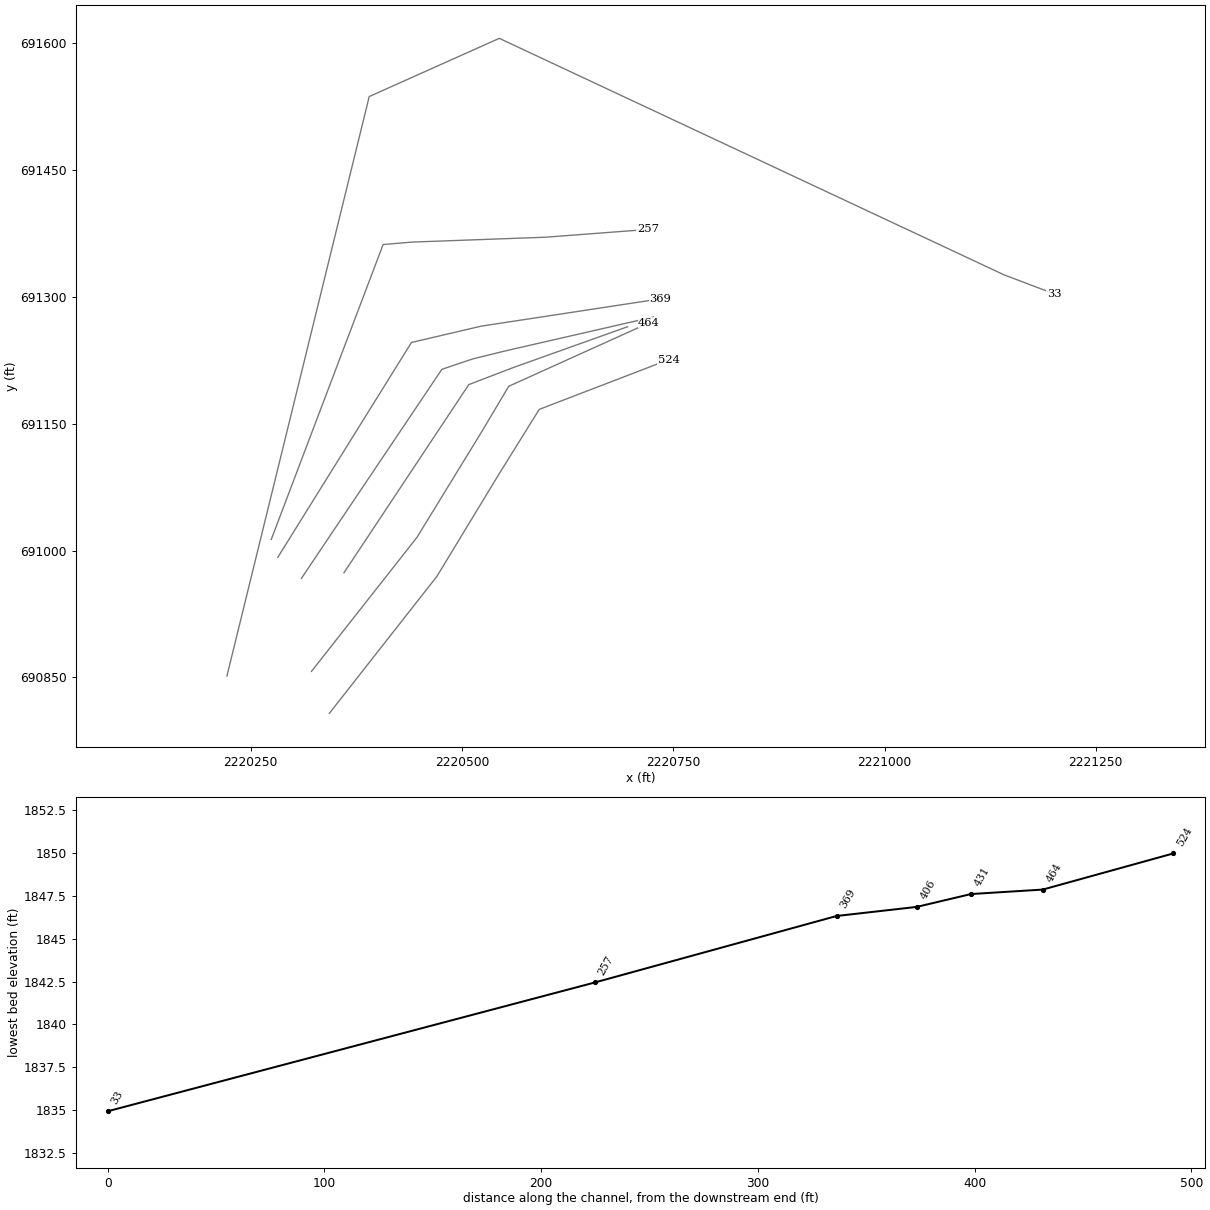
HEC-RAS study OSBORNERN.prj: OSBORNERN

--- OSBORNERN.g01 (geometry) --- (continued)

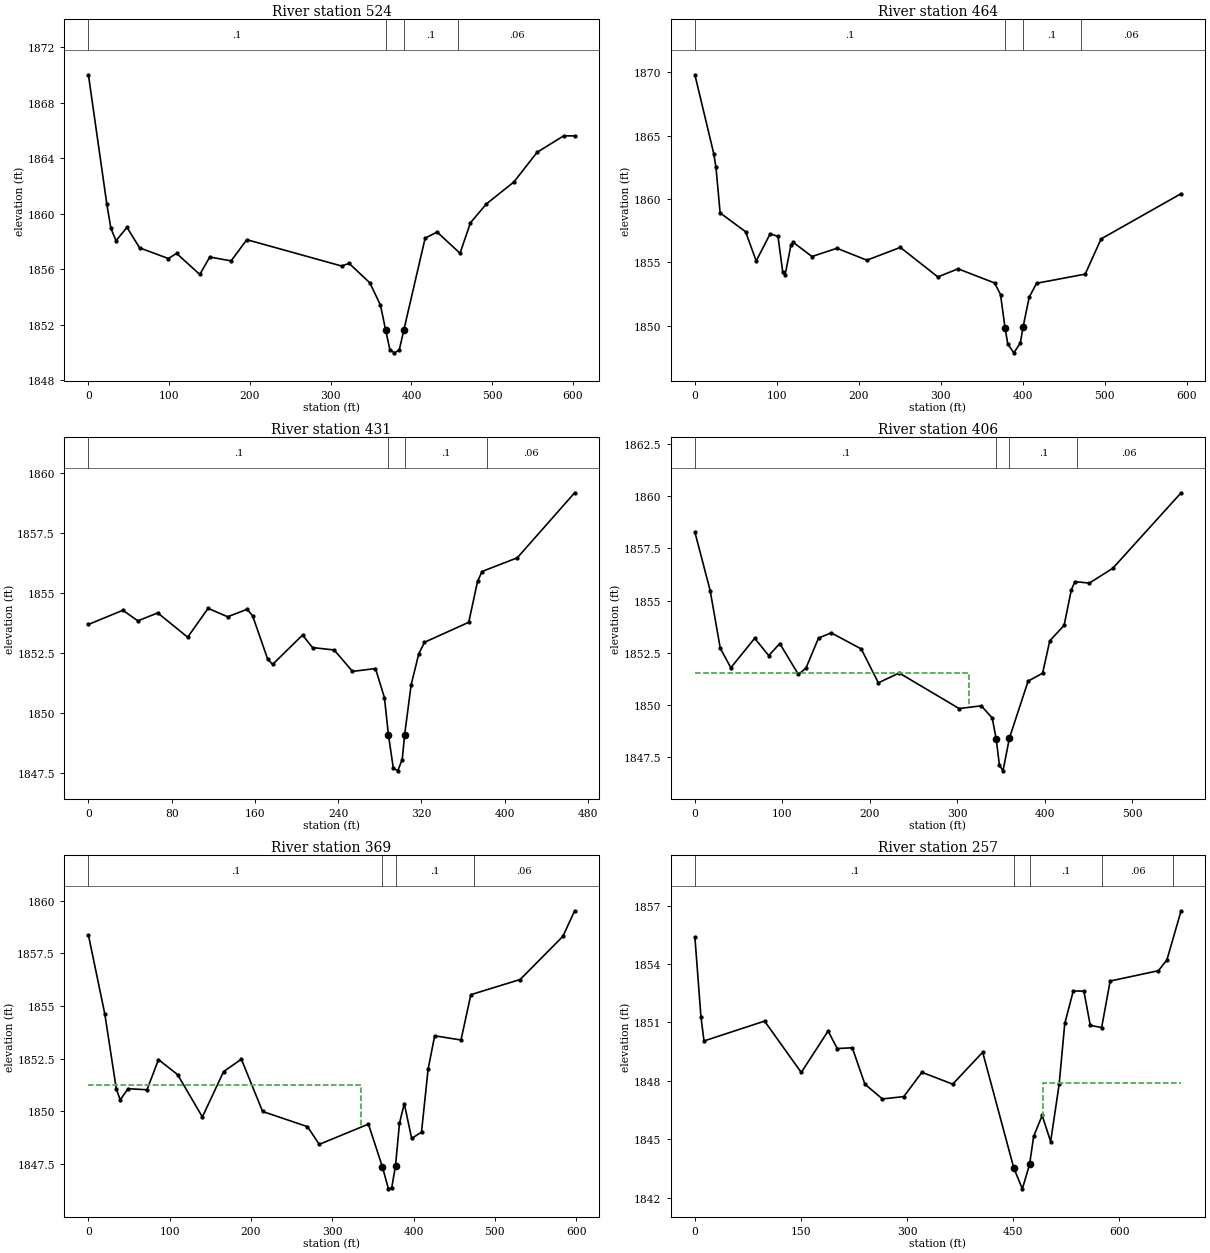
Type RM Length L Ch R = 1 ,524     ,60.2,60.3,60.8
XS GIS Cut Line= 5
2220343.03923428690807.2763856052220470.34344729690969.398562725
2220542.08515643  691087.64415742220591.44738366 691167.01087569
2220744.60963894691225.855362893
#Sta/Elev= 30
       0 1870.03    22.8  1860.7    27.8 1858.96    34.2 1858.06    47.7 1859.03
    63.4 1857.55      99 1856.78   109.2 1857.15   137.9 1855.63   150.3 1856.89
   176.7 1856.61   196.1 1858.14   313.5 1856.24   322.8 1856.43   348.4 1855.03
   361.6 1853.42     3681851.614   373.2 1850.22   378.7 1849.98   384.8 1850.17
   390.6 1851.65   416.9 1858.25   431.7 1858.69   460.1 1857.16     473 1859.36
   492.8 1860.72   526.8  1862.3   555.5 1864.44   588.5 1865.63     602 1865.62
#Mann= 4 ,-1,0
       0      .1       0     368    .045       0   390.6      .1       0
   457.9     .06       0
Bank Sta=368,390.6
XS Rating Curve= 0 ,0
Exp/Cntr(USF)=0,0
Exp/Cntr=0.3,0.1

Type RM Length L Ch R = 1 ,464     ,43.5,33.1,21.3
XS GIS Cut Line= 5
2220321.94123763690856.9880199722220446.82379785691015.653873299
2220524.28862168691142.1245700722220555.33455895691194.338191839
2220721.30328967691269.391268347
#Sta/Elev= 30
       0 1869.81      23 1863.59    25.7 1862.52    30.8 1858.91    61.8 1857.43
    74.8 1855.12    91.9 1857.27   101.4 1857.05   107.1 1854.28     110 1853.99
   117.3 1856.41     120 1856.59   142.8 1855.47   173.3 1856.12   209.8 1855.18
   250.6 1856.19   296.4 1853.86     321  1854.5   365.7 1853.38   372.8 1852.47
   378.4 1849.81   381.7 1848.56   389.1 1847.87     397 1848.65  400.251849.882
   407.8 1852.26   416.8 1853.36   476.1 1854.08   495.5 1856.86   593.1 1860.43
#Mann= 4 ,-1,0
       0      .1       0   378.4    .045       0  400.25      .1       0
  470.97     .06       0
Bank Sta=378.4,400.25
XS Rating Curve= 0 ,0
Exp/Cntr(USF)=0,0
Exp/Cntr=0.3,0.1

Type RM Length L Ch R = 1 ,431     ,26.4,25,23.2
XS GIS Cut Line= 4
2220360.35912814690973.6350928992220508.03611409691196.307914975
2220559.88508721691216.2142171562220695.98864166 691264.82262946
#Sta/Elev= 30
       0 1853.69    33.1 1854.28    47.5 1853.84    66.6 1854.17    95.4 1853.16
     115 1854.36   133.8 1854.01   152.5 1854.32   157.8 1854.05   172.2 1852.26
     177 1852.03   205.8 1853.25   215.4 1852.73   236.2 1852.63   253.8 1851.74
   275.9 1851.86   284.5 1850.65   288.31849.118     293 1847.73   297.3 1847.61
   301.6 1848.08   303.91849.108   310.2 1851.19   317.5 1852.47     323 1852.95
   365.5 1853.78     374 1855.48   378.3 1855.89   412.2 1856.46   467.3 1859.16
#Mann= 4 ,-1,0
       0      .1       0   288.3    .045       0   303.9      .1       0
  382.73     .06       0
Bank Sta=288.3,303.9
XS Rating Curve= 0 ,0
Exp/Cntr(USF)=0,0
Exp/Cntr=0.3,0.1

Type RM Length L Ch R = 1 ,406     ,37.5,37,36.8
XS GIS Cut Line= 5
2220310.02053605 690967.05353475  2220476.234198691214.435880303
2220512.58948002691226.681007104  2220552.412269691236.467963718
2220726.59924918691276.388037781
#Sta/Elev= 30
       0 1858.28    17.5 1855.48      29 1852.73    41.1 1851.79    68.4  1853.2
    84.5 1852.37    97.1 1852.95   118.4 1851.47     127 1851.77   141.4 1853.21
   155.9 1853.46   190.3 1852.69   209.8 1851.07   233.7 1851.54   302.2 1849.84
   327.5 1849.97   340.1 1849.39   344.7 1848.36   348.3 1847.13   352.4 1846.86
   359.7 1848.42   381.1 1851.15   397.7 1851.53   405.9 1853.08   422.3 1853.82
   430.5 1855.51   434.6 1855.91   451.2 1855.84     478 1856.55   556.1 1860.16
#Mann= 4 ,-1,0
       0      .1       0   344.7    .045       0   359.7      .1       0
  437.41     .06       0
#XS Ineff= 2 , 0
          313.35 1851.55
Permanent Ineff=
       F       F
Bank Sta=344.7,359.7
XS Rating Curve= 0 ,0
Exp/Cntr(USF)=0,0
Exp/Cntr=0.3,0.1

Type RM Length L Ch R = 1 ,369     ,113.4,111.6,108.6
XS GIS Cut Line= 4
2220282.13443798690991.9976906642220440.24913435691246.187407053
 2220522.7139179691265.4913522982220734.39972246691297.762490402
#Sta/Elev= 30
       0 1858.37    20.2 1854.62    34.3 1851.07    39.1 1850.55    48.8 1851.08
    72.1 1851.03    86.2 1852.46   109.7 1851.75   140.2 1849.74   166.3 1851.89
   188.2 1852.48   214.3    1850   269.5 1849.28     284 1848.44   344.5  1849.4
   361.61847.384   369.1 1846.33   373.2 1846.39  377.811847.425   382.7 1849.44
   388.6 1850.37   397.7 1848.72   409.8 1849.02   417.9    1852     426 1853.59
   458.4 1853.39   470.5 1855.54   531.2 1856.26   583.8 1858.31   598.2 1859.52
#Mann= 4 ,-1,0
       0      .1       0   361.6    .045       0  377.81      .1       0
  474.05     .06       0
#XS Ineff= 2 , 0
          335.66 1851.24
Permanent Ineff=
       F       F
Bank Sta=361.6,377.81
XS Rating Curve= 0 ,0
Exp/Cntr(USF)=0,0
Exp/Cntr=0.3,0.1

Type RM Length L Ch R = 1 ,257     ,224.7,224.7,224.7
XS GIS Cut Line= 5
2220274.34760156691013.1008370332220406.69667123691362.063071369
2220440.47519973 691364.951405122220599.30614611691370.774052645
2220720.19510182691379.948879314
#Sta/Elev= 30
       0  1855.4     8.6 1851.28    12.9 1850.05    98.5 1851.07   150.4 1848.43
   188.3 1850.56   201.2 1849.66   222.5  1849.7   240.3 1847.83   265.1 1847.07
   295.3 1847.19   320.9 1848.44   364.4 1847.83   406.8 1849.47   450.8 1843.52
   462.9 1842.45   473.1 1843.71   478.9 1845.15   490.9 1846.22   502.9 1844.88
   514.9 1847.82   522.9 1850.96   534.9 1852.62   549.9 1852.61   558.9 1850.85
     575 1850.74     587 1853.13   655.2 1853.66   667.2 1854.21   687.3 1856.74
#Mann= 5 ,-1,0
       0      .1       0   450.8    .045       0   473.1      .1       0
  576.06     .06       0  676.06     .05       0
#XS Ineff= 2 , 0
                          491.77         1847.91
Permanent Ineff=
       F       F
Bank Sta=450.8,473.1
XS Rating Curve= 0 ,0
Exp/Cntr(USF)=0,0
Exp/Cntr=0.3,0.1

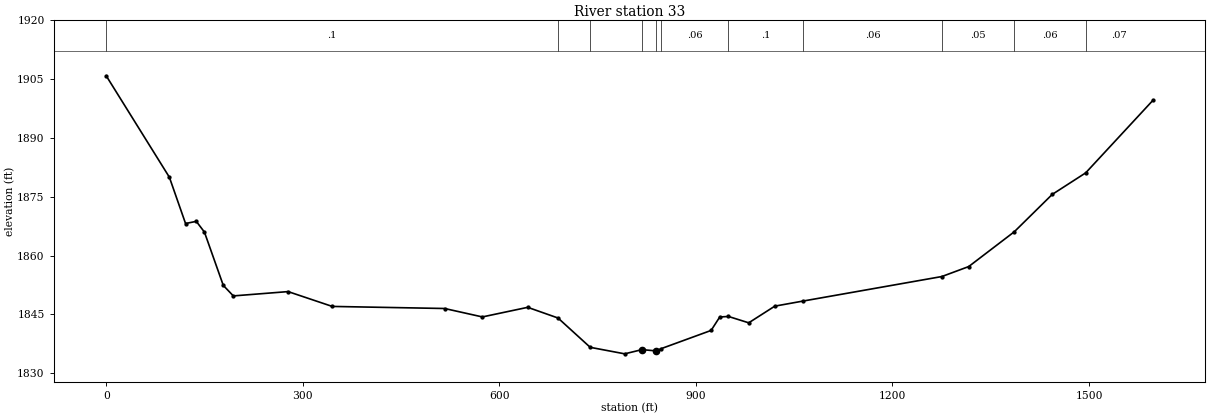
Type RM Length L Ch R = 1 ,33      ,,,
XS GIS Cut Line= 5
2220221.89943088690851.6077047132220390.28033214691537.200084084
 2220544.1781999691606.0897841112221141.26832233691326.281860626
2221200.85490637691303.683633426
#Sta/Elev= 30
       0 1905.84    96.4 1879.98   121.1 1868.17   137.5 1868.72   149.9 1865.99
   178.7 1852.39     194 1849.71   277.6 1850.81     345 1847.03   516.5  1846.5
   574.1 1844.35   643.3  1846.8   689.5 1844.08   738.7  1836.6   791.3 1834.94
   817.6 1836.01   839.5 1835.69   846.6 1836.24   923.2 1840.91   936.4 1844.34
   949.7 1844.47   980.6 1842.85  1020.4  1847.1  1063.9 1848.41  1275.3 1854.65
  1316.3 1857.19  1385.8 1866.05  1443.8 1875.59  1494.9 1881.09  1597.7 1899.62
#Mann= 11 ,-1,0
       0      .1       0   689.5     .06       0   738.7      .1       0
   817.6    .045       0   839.5      .1       0   846.6     .06       0
   949.7      .1       0  1063.9     .06       0  1275.3     .05       0
  1385.8     .06       0  1494.9     .07       0
Bank Sta=817.6,839.5
XS Rating Curve= 0 ,0
Exp/Cntr(USF)=0,0
Exp/Cntr=0.3,0.1
LCMann Table=0

Chan Stop Cuts=-1
Use User Specified Reach Order=0
Composite Channel Slope=5